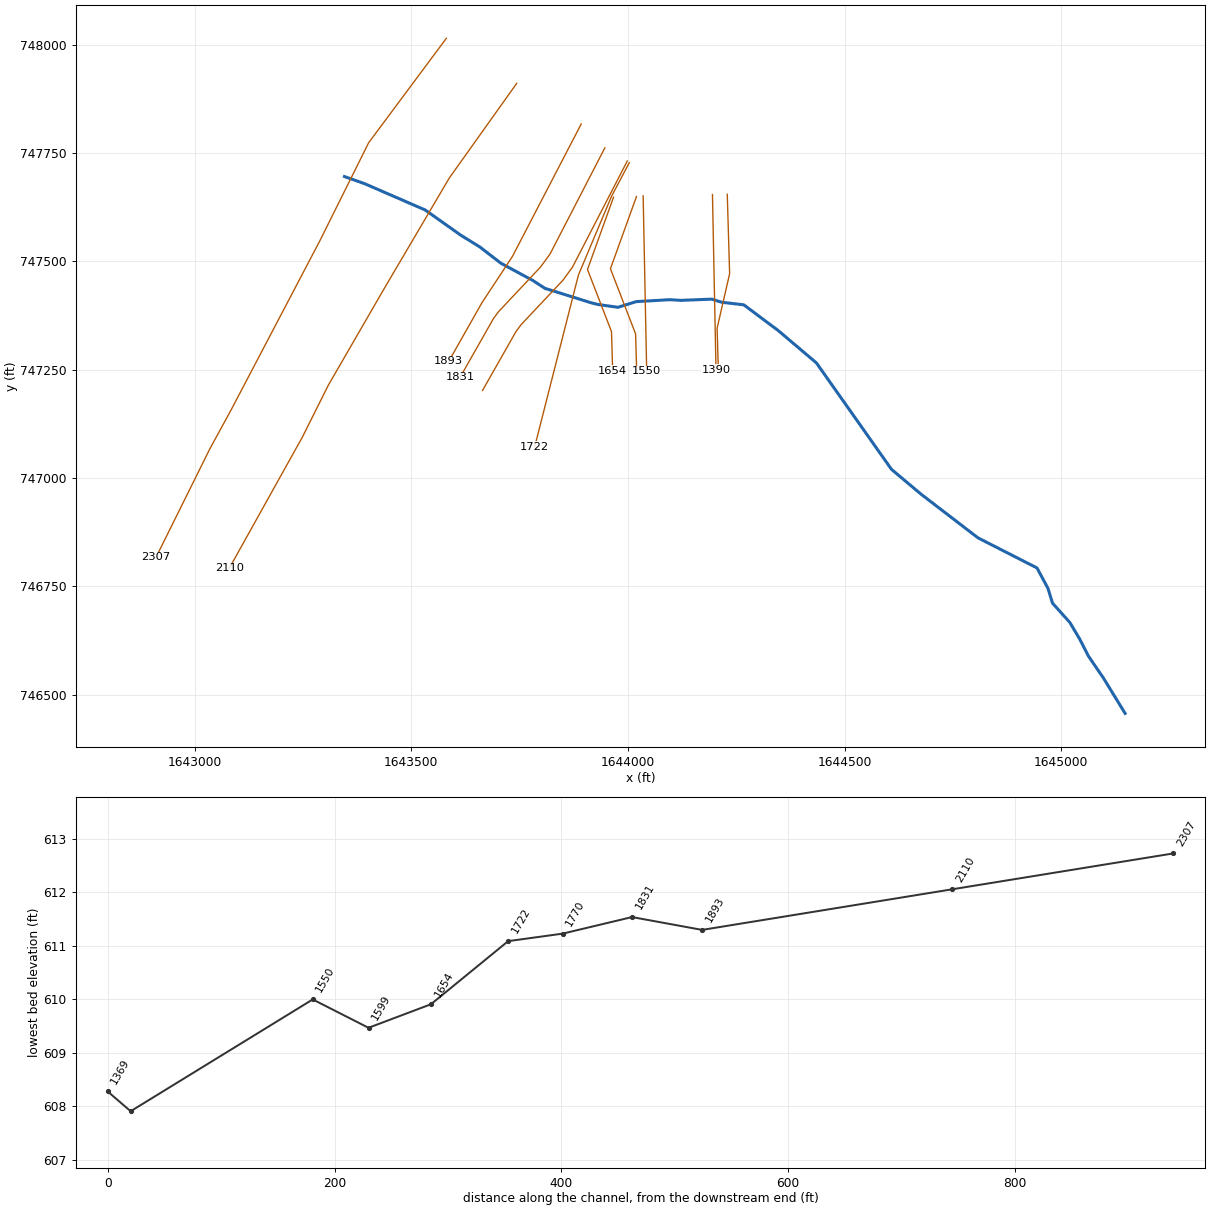
--- 105889_LUC23.prj (project) ---

Proj Title=105889_LUC-23
Current Plan=p02
Default Exp/Contr=0.3,0.1
English Units
Geom File=g02
Geom File=g01
Flow File=f01
Plan File=p01
Plan File=p02
Y Axis Title=Elevation
X Axis Title(PF)=Main Channel Distance
X Axis Title(XS)=Station
BEGIN DESCRIPTION:
END DESCRIPTION:
DSS File=..\..\..\..\400-Engineering\Structures\SFN_4801296\Hydraulics\HECRAS\105889_LUC-23.dss
DSS Export Rating Curves= 0
DSS Export Rating Curve Sorted= 0
DSS Export Volume Flow Curves= 0
DXF Filename=..\..\..\..\400-Engineering\Structures\SFN_4801296\Hydraulics\HECRAS\105889_LUC-23.
DXF OffsetX= 0
DXF OffsetY= 0
DXF ScaleX= 1
DXF ScaleY= 10

--- 105889_LUC23.p02 (plan) ---

Plan Title=LUC23-PR
Program Version=6.31
Short Identifier=LUC23-PR
Geom File=g01
Flow File=f01
Subcritical Flow
K Sum by GR= 0
Std Step Tol= 0.01
Critical Tol= 0.01
Num of Std Step Trials= 20
Max Error Tol= 0.3
Flow Tol Ratio= 0.001
Split Flow NTrial= 30
Split Flow Tol= 0.02
Split Flow Ratio= 0.02
Log Output Level= 0
Friction Slope Method= 1
Unsteady Friction Slope Method= 2
Unsteady Bridges Friction Slope Method= 1
Parabolic Critical Depth
Global Vel Dist= 0 , 0 , 0
Global Log Level= 0
CheckData=True
Encroach Param=-1 ,0,0, 0
Computation Interval=1MIN
Output Interval=1HOUR
Instantaneous Interval=1HOUR
Mapping Interval=1HOUR
Computation Time Step Use Courant=        0
Computation Time Step Use Time Series=    0
Computation Time Step Count To Double=0
Computation Time Step Max Doubling=0
Computation Time Step Max Halving=0
Computation Time Step Residence Courant=0
Run HTab= 0
Run UNet= 0
Run Sediment= 0
Run PostProcess= 0
Run WQNet= 0
Run RASMapper= 0
UNET Theta= 1
UNET Theta Warmup= 1
UNET ZTol= 0.02
UNET ZSATol= 0.02
UNET MxIter= 20
UNET Max Iter WO Improvement= 0
UNET MaxInSteps= 0
UNET DtIC= 0
UNET DtMin= 0
UNET MaxCRTS= 20
UNET WFStab= 2
UNET SFStab= 1
UNET WFX= 1
UNET SFX= 1
UNET Gravity=32.174
UNET 1D Methodology=Finite Difference
UNET DSS MLevel= 4
UNET Pardiso=0
UNET DZMax Abort= 100
UNET Use Existing IB Tables=-1
UNET Froude Reduction=False
UNET Froude Limit= 0.8
UNET Froude Power= 4
UNET D1 Cores= 0
UNET WindReference=Eulerian
UNET WindDragFormulation=Hsu (1988)
UNET D2 Coriolis=0
UNET D2 Cores= 0
UNET D2 Theta= 1
UNET D2 Theta Warmup= 1
UNET D2 Z Tol= 0.01
UNET D2 Volume Tol= 0.01
UNET D2 Max Iterations= 20
UNET D2 Equation= 0
UNET D2 RampUpFraction=0.1
UNET D2 TimeSlices= 1
UNET D2 Turbulence Formulation=None
UNET D2 Eddy Viscosity=0.3
UNET D2 Transverse Eddy Viscosity=0.1
UNET D2 Smagorinsky Mixing=0.05
UNET D2 BCVolumeCheck=0
UNET D2 Cores=0
UNET D2 SolverType=PARDISO (Direct)
UNET D2 Minimum Iterations= 2147483647
UNET D2 Maximum Iterations= 2147483647
UNET D2 Restart Number= 10
UNET D2 Relaxation Coeff=1.3
UNET D2 SOR Precondition Iterations= 10
UNET D2 ILUT Maximum Fill= 8
UNET D2 ILUT Tolerance=1E-08
UNET D1D2 MaxIter= 0
UNET D1D2 ZTol=0.01
UNET D1D2 QTol=0.1
UNET D1D2 MinQTol=1
DSS File=dss
Write IC File= 0
Write IC File at Fixed DateTime=0
Write IC File at Sim End=0
Echo Input=False
Echo Parameters=False
Echo Output=False
Write Detailed= 0
HDF Write Warmup=0
HDF Write Time Slices=0
HDF Flush=0
HDF Compression= 1
HDF Chunk Size= 1
HDF Spatial Parts= 1
HDF Use Max Rows=0
HDF Fixed Rows= 1
Calibration Method= 0
Calibration Iterations= 20
Calibration Max Change=0.05
Calibration Tolerance=0.2
Calibration Maximum=1.5
Calibration Minimum=0.5
Calibration Optimization Method= 1
WQ AD Non Conservative
WQ ULTIMATE=-1
WQ Max Comp Step=1HOUR
WQ Output Interval=15MIN
WQ Output Selected Increments= 0
WQ Create Restart=0
WQ Fixed Restart=0
WQ System Summary=0
WQ Write To DSS=0
Sorting and Armoring Iterations= 10
XS Update Threshold= 0.02
Bed Roughness Predictor= 0
Hydraulics Update Threshold= 0.02
Energy Slope Method= 0
Volume Change Method= 1
Sediment Retention Method= 0
Sediment TS Multiplier= 1
Warm Up Method= 0
XS Weighting Method= 0
Number of US Weighted Cross Sections= 1
Number of DS Weighted Cross Sections= 1
Upstream XS Weight=0
Main XS Weight=1
Downstream XS Weight=0
Number of DS XS's Weighted with US Boundary= 1
Upstream Boundary Weight= 1
Weight of XSs Associated with US Boundary= 0
Number of US XS's Weighted with DS Boundary= 1
Downstream Boundary Weight= 0.5
Weight of XSs Associated with DS Boundary= 0.5
Percentile Method= 0
Sediment Output Level= 3
Mass or Volume Output= 0
Output Increment Type= 1
Profile and TS Output Increment= 1
Transport Output Increment 1
XS Output Flag= 0
XS Output Increment= 10
Read HDF5 Sediment Hotstart= 0
Sediment Hotstart Type= 0
Write Gradation File= 0
Read Gradation Hotstart= 0
Write HDF5 File= 1
Write Binary Output= 1
Write DSS Sediment File= 0
DSS Sediment Output Type= 1
SV Curve= 0
Specific Gage Flag= 0
Subcell Erosion Methods= 0
Subcell Deposition Methods= 0
Advection Scheme= 1
Matrix Solver= 0
Implicit Weighting Factor= 1
Maximum Outer Loop Convergence Iterations= 5
Convergence Maximum Absolute= 0.001
Convergence RMSE= 0.0001
Grain Fractions Max Abs Error= 0.001
Max Subgrid Regions= 1
Max Subgrid Length Scale= 3.402823E+38
Initial Layer Thickness= 3.402823E+38
Min Layer Thickness= 3.402823E+38
Max Layer Thickness= 3.402823E+38
Number of Layers= 5

--- 105889_LUC23.p01 (plan) ---

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Plan Title=LUC23_Existing
Short Identifier=LUC23_EX
Geom File=g02
Flow File=f01

--- 105889_LUC23.f01 (steady flow) ---

Flow Title=STDY_FLOW_DATA
Program Version=6.30
Number of Profiles= 7
Profile Names=2-YR,5-YR,10-YR,25-YR,50-YR,100-YR,500-YR
River Rch & RM=Ottawa River,Reach           ,2307
    2290    3280    3960    4840    5510    6190    7780
Boundary for River Rch & Prof#=Ottawa River,Reach           , 1
Up Type= 0
Dn Type= 3
Dn Slope=0.00213
Boundary for River Rch & Prof#=Ottawa River,Reach           , 2
Up Type= 0
Dn Type= 3
Dn Slope=0.00213
Boundary for River Rch & Prof#=Ottawa River,Reach           , 3
Up Type= 0
Dn Type= 3
Dn Slope=0.00213
Boundary for River Rch & Prof#=Ottawa River,Reach           , 4
Up Type= 0
Dn Type= 3
Dn Slope=0.00213
Boundary for River Rch & Prof#=Ottawa River,Reach           , 5
Up Type= 0
Dn Type= 3
Dn Slope=0.00213
Boundary for River Rch & Prof#=Ottawa River,Reach           , 6
Up Type= 0
Dn Type= 3
Dn Slope=0.00213
Boundary for River Rch & Prof#=Ottawa River,Reach           , 7
Up Type= 0
Dn Type= 3
Dn Slope=0.00213
DSS Import GetInterval= 0
DSS Import GetPeak= 0
DSS Import FillOption= 0

--- 105889_LUC23.g01 (geometry) ---

Geom Title=LUC-23_PR
Program Version=6.31

River Reach=Ottawa River    ,Reach
Reach XY= 30
      1643345.94       747695.821643392.99225773747679.120536069
1643532.23903092747618.6410288361643613.84748246747560.876886981
1643659.04313484747532.8456741991643706.84060639747495.844244739
       1643780.2       747456.23      1643808.66       747437.81
      1643914.56       747404.66      1643929.86       747400.68
      1643976.97       747394.02      1644019.39       747407.14
       1644097.5       747411.65      1644122.04       747410.02
      1644193.88       747412.86      1644216.38       747405.72
       1644267.5       747399.78      1644346.28       747340.98
      1644435.09       747265.77      1644608.43       747020.06
       1644676.3       746963.04       1644808.1       746861.93
      1644944.16        746792.6      1644969.51       746745.54
      1644980.02       746711.27      1645019.87        746666.9
      1645042.81       746628.38      1645062.99       746588.93
      1645096.93       746539.39      1645147.54       746456.92

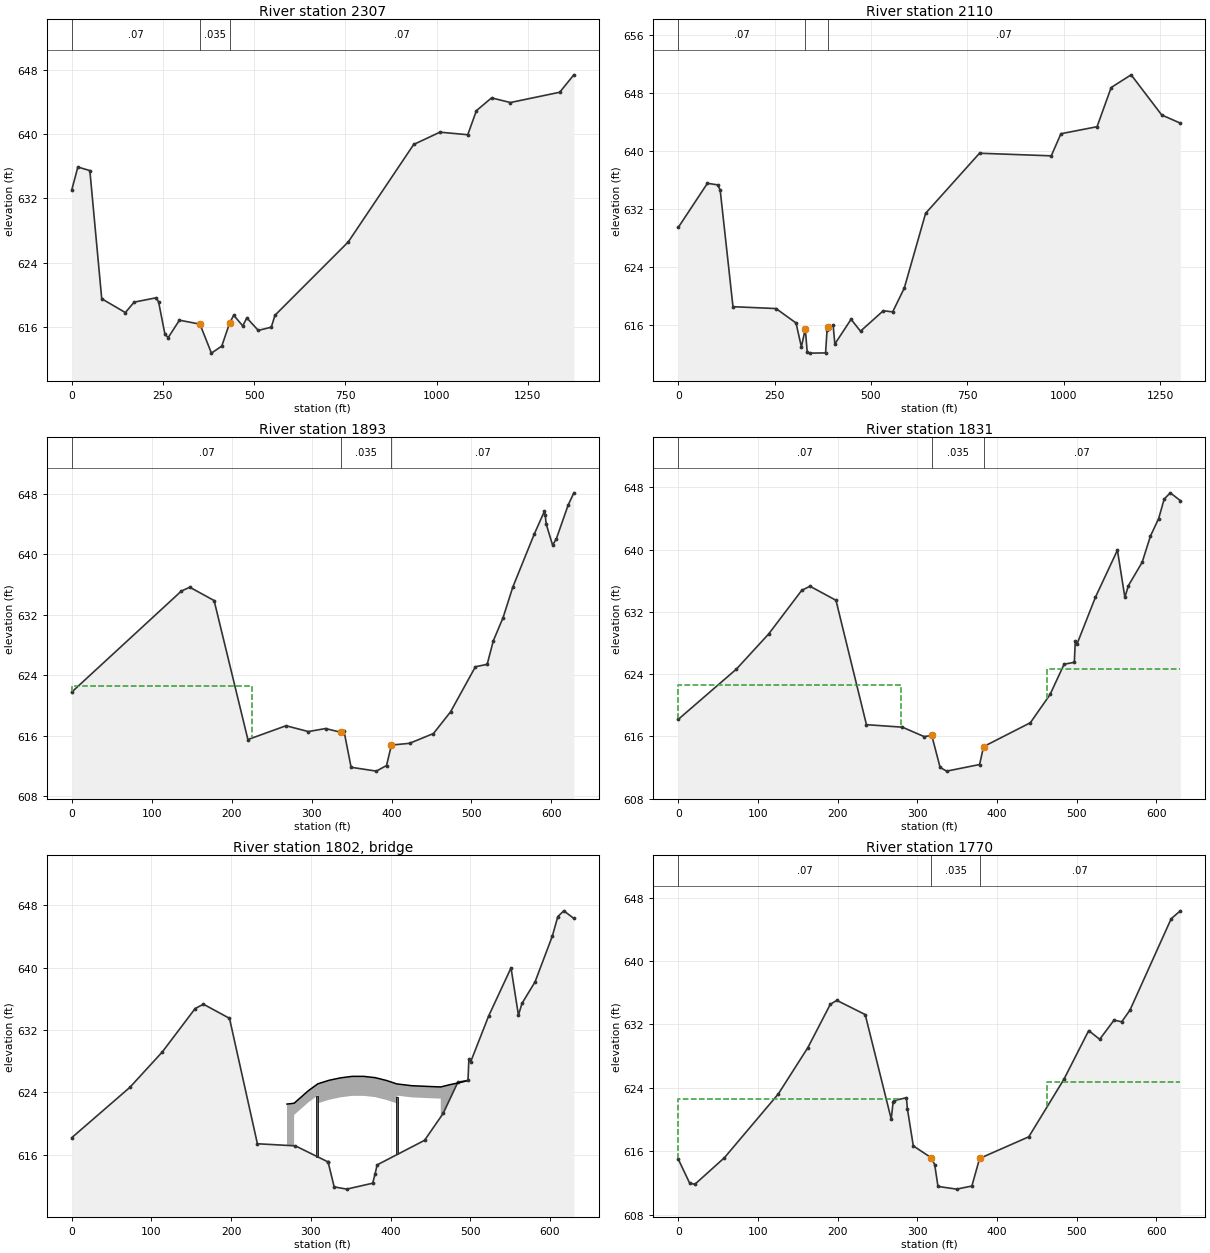
Type RM Length L Ch R = 1 ,2307    ,199.13,194.8,185.9
XS GIS Cut Line= 6
1643581.13075117748014.7312732611643401.75901531747773.626241877
1643289.41424645 747547.856432251643082.76194768747154.072091933
1643035.71829695747068.095764735 1642911.0769413746816.887948785
#Sta/Elev= 30
       0  633.05   16.64   635.9   49.55  635.46   82.09   619.5  146.83  617.78
  170.94  619.08   231.1  619.62  237.88  619.12  255.44  615.05   264.3  614.67
     295  616.83  351.25  616.34  382.77  612.73   411.1  613.61   432.7 616.487
  443.82  617.45  468.54  616.12  479.72  617.12  511.03  615.56  546.81  615.96
  556.93  617.45  757.61  626.57  937.01  638.71 1008.92  640.24 1085.15  639.92
 1108.88  642.92  1150.4  644.51 1201.95  643.93 1337.08  645.21 1375.89  647.38
#Mann= 3 ,0,0
       0     .07       0  351.25    .035       0   432.7     .07       0
Bank Sta=351.25,432.7
XS Rating Curve= 0 ,0
Exp/Cntr=0.3,0.1

Type RM Length L Ch R = 1 ,2110    ,213.75,220.7,210.7
XS GIS Cut Line= 6
1643743.54382237747910.7896994671643588.31002458747692.930452251
1643434.92529538747432.4483916751643308.78776383747214.233491164
1643248.70647299747094.0709094771643080.13554265746791.661712566
#Sta/Elev= 30
       0   629.4   75.71   635.5  102.58  635.28  108.86  634.54  142.02  618.47
  253.75  618.21  305.57  616.22   319.5  612.91  329.58  615.43  334.58  612.18
  340.53  612.06  382.17  612.09  386.11  615.28  388.74  615.65  401.89  615.91
  406.27  613.32  448.31  616.73  472.82  615.09  531.95  617.91  556.24  617.75
  586.33  621.03  641.74  631.36  781.52  639.65   967.7  639.29   992.7  642.34
 1086.45  643.31 1123.03  648.72 1174.84  650.47 1254.18  644.93 1302.42   643.8
#Mann= 3 ,0,0
       0     .07       0  329.58    .035       0  388.74     .07       0
Bank Sta=329.58,388.74
XS Rating Curve= 0 ,0
Exp/Cntr=0.3,0.1

Type RM Length L Ch R = 1 ,1893    ,74.58,61.8,46.7
XS GIS Cut Line= 4
1643892.34592037747816.9993893851643733.62045148747511.358742855
1643663.54337893747404.9867723521643586.48601673747268.992013356
#Sta/Elev= 30
       0  621.77  137.17  635.15  147.65  635.65  178.06  633.89  220.33  615.48
  268.03  617.31  295.98  616.54  317.61  616.94  336.89 616.432  340.48  616.64
  349.46  611.81  381.01   611.3  393.77  612.04  399.88 614.753  422.51  614.98
  452.48  616.28  473.91  619.16  504.94  625.12  519.66  625.44  527.39  628.57
  539.56  631.63  551.73  635.67   578.5  642.67  591.15  645.68   592.3  645.28
  593.45  644.04  601.49  641.23  606.09  642.03  620.91  646.51  628.09  648.15
#Mann= 3 ,0,0
       0     .07       0  336.89    .035       0  399.88     .07       0
#XS Ineff= 2 ,-1
       0  225.42 622.604  514.16 628.087  624.69
Permanent Ineff=
       F       F
Bank Sta=336.89,399.88
XS Rating Curve= 0 ,0
Exp/Cntr(USF)=0,0
Exp/Cntr=0.5,0.3

Type RM Length L Ch R = 1 ,1831    ,61.2,61.2,61.2
XS GIS Cut Line= 6
1643946.93118752 747761.929025931643820.59901614747517.330771878
1643798.69881424747487.1228856691643701.66442316747383.993529173
1643690.05410812747368.3274663981643612.90734924747232.528901836
#Sta/Elev= 30
       0  618.19   72.93  624.65  113.45  629.17  154.82  634.76  165.21  635.31
  197.87   633.5  236.13  617.51  281.21  617.19  308.47  615.98  318.08  616.12
  328.57  612.01  336.82  611.54  378.09  612.39  383.04  614.69  441.76  617.76
  466.49  621.39  484.07  625.28  496.94  625.53  498.09  628.23  500.39   627.9
  523.39  633.89  550.99  639.94  560.34  633.88  564.79  635.39  582.05  638.39
   592.4  641.75  602.75  644.01  609.65  646.51   617.3  647.31  629.89  646.31
#Mann= 3 ,0,0
       0     .07       0  318.08    .035       0  383.04     .07       0
#XS Ineff= 2 , 0
          278.96 622.604  462.93         624.697
Permanent Ineff=
       F       F
Bank Sta=318.08,383.04
XS Rating Curve= 0 ,0
Exp/Cntr=0.5,0.3

Type RM Length L Ch R = 3 ,1802    ,,,
BEGIN DESCRIPTION:
Pedestrian Bridge
END DESCRIPTION:
Bridge Culvert--1,0,-1,-1, 0
Deck Dist Width WeirC Skew NumUp NumDn MinLoCord MaxHiCord MaxSubmerge Is_Ogee
21.76832,13.5,2.6,0, 19, 19, , , 0.98, 0, 0,0,,
  270.03  278.96  296.75  308.95  309.28  322.84  337.08  351.69  366.27  380.61
  394.84  408.06  408.73  426.09  444.87  462.93  473.72  484.16  494.39
 622.504 622.604  624.21 625.116 625.116 625.554 625.862 626.056 626.056 625.891
 625.527 625.077 625.077  624.86 624.772 624.697 624.974 625.202 625.444
         621.104  622.71 623.616 622.616 623.054 623.362 623.556 623.556 623.391
 623.027 622.577 623.577  623.36 623.272 623.197
  270.03  278.96  296.75  308.95  309.28  322.84  337.08  351.69  366.27  380.61
  394.84  408.06  408.73  426.09  444.87  462.93  473.72  484.16  494.39
 622.504 622.604  624.21 625.116 625.116 625.554 625.862 626.056 626.056 625.891
 625.527 625.077 625.077  624.86 624.772 624.697 624.974 625.202 625.444
         621.104  622.71 623.616 622.616 623.054 623.362 623.556 623.556 623.391
 623.027 622.577 623.577  623.36 623.272 623.197
Pier Skew, UpSta & Num, DnSta & Num=  ,307.95, 2 ,307.95, 2 , 0 , 0 , 0 ,,
     2.5     2.5
       0 625.116
     2.5     2.5
       0 625.116
Pier Skew, UpSta & Num, DnSta & Num=  ,408.61, 2 ,408.61, 2 , 0 , 0 , 0 ,,
     2.5     2.5
       0 625.077
     2.5     2.5
       0 625.077
BR Coef=-1 , 0 , 0 ,, 0 ,,,0.8,0,,0,
WSPro=,,,, 1 ,,,, 0 ,,,, 0 ,,,,-1 ,-1 ,-1 , 0 , 0 , 0 , 0 , 0
BR U #Sta/Elev= 30
       0  618.19   72.93  624.65  113.45  629.17  154.82  634.76  165.21  635.31
  197.87   633.5   232.9  617.41   280.6  617.14  321.25 615.091   321.6  615.07
   329.2  611.88   344.9  611.59   377.5  612.35  380.45 613.498   383.1   614.7
   442.6  617.85     466  621.31   484.4  625.31   497.1  625.53   498.2  628.23
   500.5  627.93     523   633.8   551.1  639.97   560.4   633.9   564.8  635.41
   581.2  638.17   602.9  644.05   609.8  646.55   617.3  647.29   629.9  646.32
BR U #Mann= 3
       0     .07  321.25     .03  380.45     .04
BR U Banks=321.6,383.1
BR D #Sta/Elev= 30
       0  615.02   14.32  611.99   20.86  611.84   57.93  615.19  125.46  623.22
   162.6  629.07  190.83  634.54  198.94  635.03  234.56  633.24  262.77  621.87
   286.4  622.76   313.4  616.77     315   615.3  317.47 615.145   327.6  611.56
   349.3  611.02   369.9  611.93  376.05 614.348   378.1  615.14   419.3  616.65
   431.4  617.89   438.6  617.98   495.5  626.87   515.1  631.28   528.9  630.12
   546.8  632.54   556.5  632.36   567.4  633.96   579.1  636.92   609.4  643.11
BR D #Mann= 3
       0     .07  317.47     .03  376.05     .04
BC Design=,, 0 ,, 0 ,,,,,,
BC Use User HTab Curves=0
BC User HTab FreeFlow(D)= 0

Type RM Length L Ch R = 1 ,1770    ,16.8,48,117.7
XS GIS Cut Line= 6
1643998.70128398 747731.60062104 1643872.3691126747487.002366987
 1643850.4689107747456.7944807791643753.43451962747353.665124283
1643741.82420458747337.999061507 1643664.6774457747202.200496946
#Sta/Elev= 30
       0  615.02   14.32  611.99   20.86  611.84   57.93  615.19  125.46  623.22
   162.6  629.07  190.83  634.54  198.94  635.03  234.56  633.24  267.22  620.06
  269.52  622.17  270.65  622.39  286.25  622.76  287.49  621.36   294.9  616.68
  317.47 615.183  321.75  614.32  325.86  611.57  349.18  611.23  368.38  611.62
   378.1   615.1  439.81  617.83  483.91  625.09  514.96  631.22  528.76  630.12
  546.73  632.54  556.37  632.33  566.72   633.8  618.47  645.33  629.89  646.32
#Mann= 3 ,0,0
       0     .07       0  317.47    .035       0   378.1     .07       0
#XS Ineff= 2 , 0
          278.96 622.604  462.93         624.697
Permanent Ineff=
       F       F
Bank Sta=317.47,378.1
XS Rating Curve= 0 ,0
Exp/Cntr=0.5,0.3

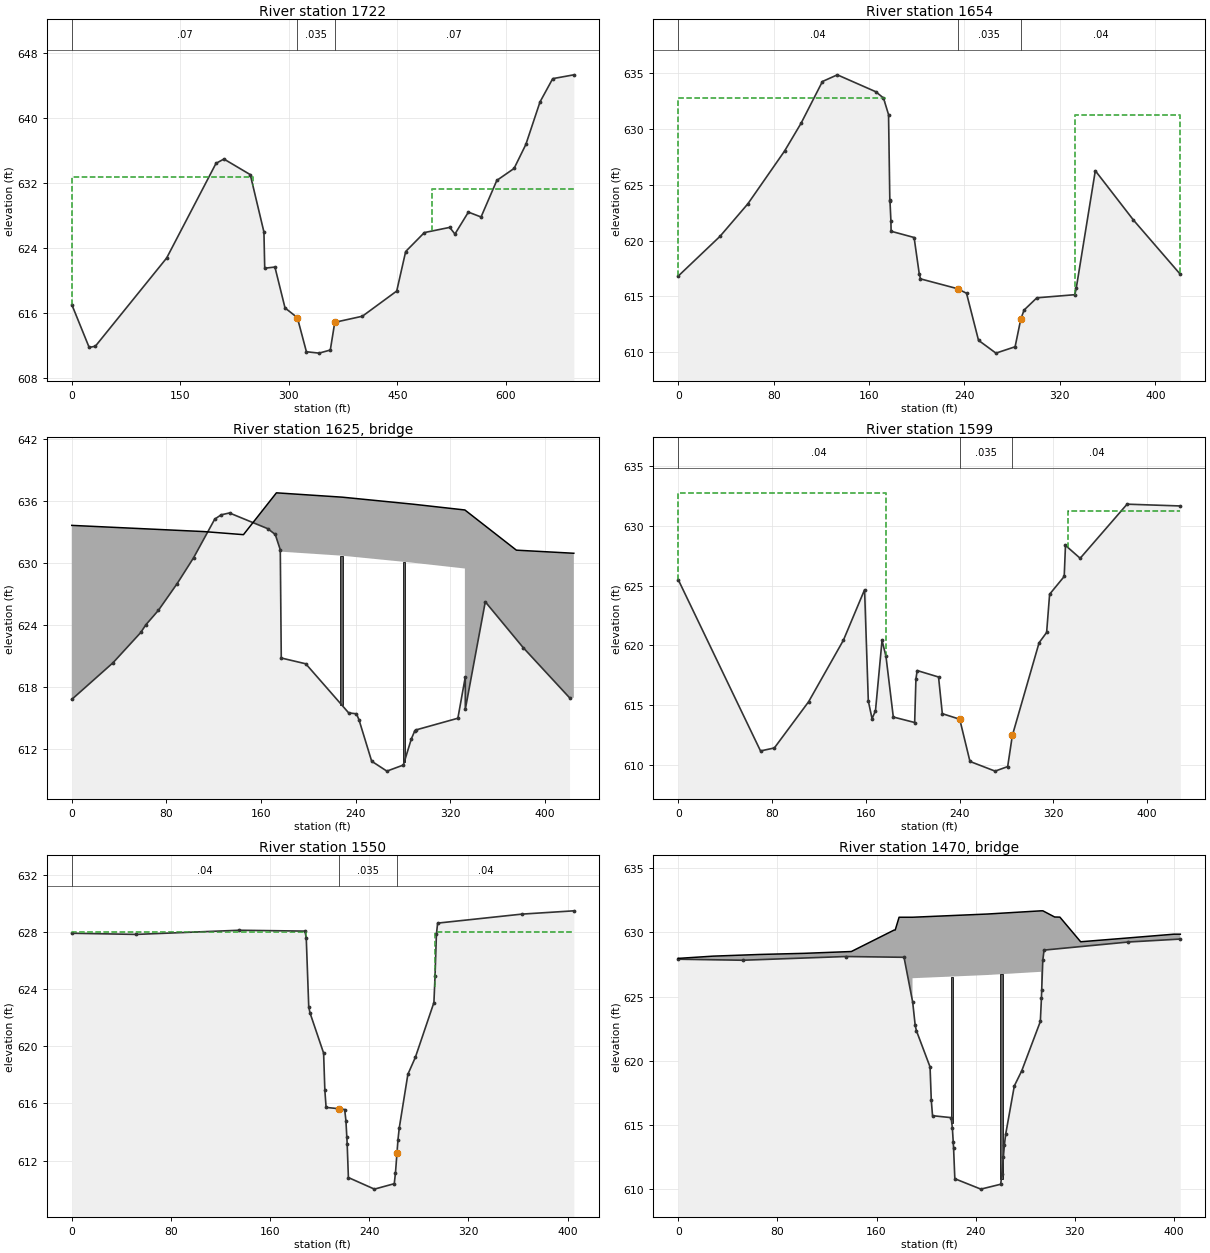
Type RM Length L Ch R = 1 ,1722    ,12.6,68.1,119.7
XS GIS Cut Line= 4
1644003.38275671 747727.722517171643962.44911272747650.365235112
1643885.93477143747468.3930929371643784.97464554747071.821027881
#Sta/Elev= 30
       0  617.07   24.06  611.79   32.62  611.94  131.17  622.79  199.44  634.44
  210.36  634.97  246.79  633.05  265.68  625.99  266.77  621.54  280.87  621.68
  294.85  616.65   311.9 615.455  324.41  611.26  341.95  611.09  357.43  611.47
  363.62  614.88   401.8  615.63  449.27  618.73  461.65  623.59  487.45  625.92
  522.53  626.56  529.75  625.74  548.33  628.44  565.87  627.84  587.66  632.34
  611.51  633.81  627.78  636.76  647.39     642  664.93  644.86  694.15  645.33
#Mann= 3 ,0,0
       0     .07       0   311.9    .035       0  363.62     .07       0
#XS Ineff= 2 , 0
          250.57  632.77  498.72          631.27
Permanent Ineff=
       F       F
Bank Sta=311.9,363.62
XS Rating Curve= 0 ,0
Exp/Cntr(USF)=0,0
Exp/Cntr=0.5,0.3

Type RM Length L Ch R = 1 ,1654    ,49.4,55,55.5
XS GIS Cut Line= 4
1643966.95270087747648.0391838811643906.88151883747481.349141579
1643962.26605081747337.8969229821643964.94487296747247.896597996
#Sta/Elev= 30
       0  616.82   34.98  620.38   58.37   623.3   89.19  628.04  103.01  630.53
   120.9  634.27   133.4  634.87  165.72  633.35   172.1  632.79  176.35   631.3
  177.42  623.63  177.54  623.58  178.32   621.8  178.49  620.84  197.78  620.28
  202.07  617.04  203.14  616.57   234.2 615.688  241.73  615.28  251.79  611.06
  266.39  609.91  282.47  610.48   287.2 612.943  289.97  613.77  300.69  614.87
  332.54  615.15  333.72  615.72  349.73  626.27  381.74  621.84     421  616.98
#Mann= 3 ,0,0
       0     .04       0   234.2    .035       0   287.2     .04       0
#XS Ineff= 2 , 0
          173.09  632.77  332.48          631.27
Permanent Ineff=
       F       F
Bank Sta=234.2,287.2
XS Rating Curve= 0 ,0
Exp/Cntr(USF)=0,0
Exp/Cntr=0.5,0.3

Type RM Length L Ch R = 3 ,1625    ,,,
BEGIN DESCRIPTION:
SB  Ramp Proposed Bridge
END DESCRIPTION:
Bridge Culvert--1,0,-1,-1, 0
Deck Dist Width WeirC Skew NumUp NumDn MinLoCord MaxHiCord MaxSubmerge Is_Ogee
12.33812,28.33,2.6,0, 11, 11, , , 0.98, 0, 0,0,,
       0  111.69   145.2  173.09  173.09  228.74  288.64  332.48  332.48  376.03
  424.63
  633.67  633.07  632.77  636.82  636.82   636.4  635.72  635.16  635.16  631.27
  630.97
                                 631.153 630.733 630.053 629.493
        
       0  111.69   145.2  177.18  177.18  222.46   283.7  332.65  332.65  376.03
  424.63
  633.67  633.07  632.77  638.05  638.05  637.56  636.87   636.3   636.3  631.27
  630.97
                                 632.383 631.893 631.203 630.633
        
Pier Skew, UpSta & Num, DnSta & Num=  ,228.25, 2 ,230.62, 2 , 0 , 0 , 0 ,,
       2       2
       0  630.75
       2       2
       0  631.89
Pier Skew, UpSta & Num, DnSta & Num=  ,281.19, 2 ,286.06, 2 , 0 , 0 , 0 ,,
       2       2
       0  630.15
       2       2
       0  631.25
BR Coef=-1 , 0 , 0 ,, 0 ,,,0.8,-1,,0,
WSPro=,,,, 1 ,,,, 0 ,,,, 0 ,,,,-1 ,-1 ,-1 , 0 , 0 , 0 , 0 , 0
BR U #Sta/Elev= 30
       0  616.82   34.98  620.38   58.37   623.3   62.62  624.04   73.25  625.44
   89.19  628.04  103.01  630.53   120.9  634.27  126.31  634.69   133.4  634.87
  165.72  633.35   172.1  632.79  176.35   631.3  177.18  620.83   197.9  620.27
   234.2 615.517  240.78  615.43  242.92  614.85  253.64  610.84   266.5  609.88
  280.44  610.47   287.2 613.007  290.08  613.77  291.16  613.87  326.55     615
  332.83     619  332.83  615.86  349.73  626.27  381.74  621.84     421  616.98
BR U #Mann= 3
       0     .04   234.2    .035   287.2     .04
BR D #Sta/Elev= 30
       0   625.5   70.18  611.16   81.98  611.41  111.21  615.28  158.95  624.66
  159.11  624.28  159.76  612.75  176.85  614.48  176.85  619.57  186.85  614.57
     190  614.14  201.79  613.52  202.86  617.66  203.93  617.88  222.15  617.35
   224.3  614.62  225.37  614.29   240.1 613.818  248.95  610.28  267.18  609.56
  281.11  609.87     285  612.48  307.27  620.04  314.34   621.1  316.71  624.27
  329.35  625.79  330.42  628.34  342.84  627.29  382.86  631.82  428.26  631.67
BR D #Mann= 3
       0     .04   240.1    .035     285     .04
BC Design=,, 0 ,, 0 ,,,,,,
BC Use User HTab Curves=0
BC User HTab FreeFlow(D)= 0

Type RM Length L Ch R = 1 ,1599    ,73.5,49.2,23.6
XS GIS Cut Line= 4
1644019.92124534747649.667262505 1643959.8500633747482.977220203
1644017.85119158747332.7477204641644020.53001373747242.747395477
#Sta/Elev= 30
       0   625.5   70.18  611.16   81.98  611.41  111.21  615.28  140.88  620.43
  158.95  624.66  162.14  615.34  165.33  613.86  168.25  614.53  173.83  620.41
  177.18  619.09  183.45     614  201.67  613.54  202.75  617.19  203.82  617.89
  222.04  617.35  225.26  614.28   240.1 613.815  248.84  610.28  270.28  609.47
     281  609.85     285 612.458   307.8  620.22  314.23  621.08  316.78  624.28
  329.23  625.77  330.31  628.37  342.84  627.29  382.86  631.82  428.26  631.67
#Mann= 3 ,0,0
       0     .04       0   240.1    .035       0     285     .04       0
#XS Ineff= 2 , 0
          177.18  632.77  332.65          631.27
Permanent Ineff=
       F       F
Bank Sta=240.1,285
XS Rating Curve= 0 ,0
Exp/Cntr(USF)=0,0
Exp/Cntr=0.5,0.3

Type RM Length L Ch R = 1 ,1550    ,160.3,160.5,160.2
XS GIS Cut Line= 2
1644035.31427805747651.1479919131644043.49036584747246.082010919
#Sta/Elev= 30
       0  627.91    52.1  627.83   135.1  628.12   188.2  628.06   189.2  627.56
   191.2  622.77   192.2  622.34   203.2  619.52   204.2  616.92   205.2  615.72
   215.4  615.63   220.2  615.57   221.2  614.79   221.9  613.68   222.2  613.18
   223.2  610.81   244.2     610   260.2  610.38   261.2  611.16   262.4612.5327
   263.2  613.45   264.2  614.26   271.2  618.04   277.2  619.22   292.2  623.06
   293.1   624.9   294.2  627.83   295.2  628.62   363.2  629.25   405.1  629.48
#Mann= 3 ,0,0
       0     .04       0   215.4    .035       0   262.4     .04       0
#XS Ineff= 2 , 0
          189.06 627.975  292.72         627.975
Permanent Ineff=
       F       F
Bank Sta=215.4,262.4
XS Rating Curve= 0 ,0
Exp/Cntr(USF)=0,0
Exp/Cntr=0.5,0.3

Type RM Length L Ch R = 3 ,1470    ,,,
BEGIN DESCRIPTION:
SB & NB Twin Bridges
END DESCRIPTION:
Bridge Culvert--1,0,-1,-1, 0
Deck Dist Width WeirC Skew NumUp NumDn MinLoCord MaxHiCord MaxSubmerge Is_Ogee
7.582219,144.4,2.6,0, 18, 18, , , 0.98, 0, 0,0,,
       0   28.07   65.48  101.94  139.69  174.16  175.11  178.21  189.06  249.35
  292.72  294.28  303.72  307.97  324.73  363.29  399.95  405.15
 627.975  628.15  628.28  628.37  628.51  630.18  630.19  631.18  631.18  631.43
  631.68  631.68   631.2  631.19  629.27  629.57  629.86  629.86
                                                                  626.43  626.68
  626.93
       0   28.07   65.48  101.94  139.69  174.16  175.11  178.21  189.06  249.35
  292.72  294.28  303.72  307.97  324.73  363.29  399.95  405.15
 627.975  628.15  628.28  628.37  628.51  630.18  630.19  631.18  631.18  631.43
  631.68  631.68   631.2  631.19  629.27  629.57  629.86  629.86
                                                                  626.43  626.68
  626.93
Pier Skew, UpSta & Num, DnSta & Num=  ,220.73, 2 ,220.73, 2 , 0 , 0 , 0 ,,
       2       2
       0     627
       2       2
       0     627
Pier Skew, UpSta & Num, DnSta & Num=  ,260.73, 2 ,260.73, 2 , 0 , 0 , 0 ,,
       2       2
       0     627
       2       2
       0     627
BR Coef=-1 , 0 , 0 ,, 0 ,,,0.8,-1,,0,
WSPro=,,,, 1 ,,,, 0 ,,,, 0 ,,,,-1 ,-1 ,-1 , 0 , 0 , 0 , 0 , 0
BR U #Sta/Elev= 30
       0  627.91    52.1  627.83   135.1  628.12   182.2  628.06   189.2  624.56
   191.2  622.77   192.2  622.34   203.2  619.52   204.2  616.92   205.2  615.72
   220.2  615.57   221.2  614.79   221.9  613.68   222.2  613.18   223.2  610.81
   244.2     610   260.2  610.38   261.2  611.16   262.4 612.533   263.2  613.45
   264.2  614.26   271.2  618.04   277.2  619.22   292.2  623.06   293.1   624.9
   293.3  625.52   294.2  627.83   295.2  628.62   363.2  629.25   405.1  629.48
BR U #Mann= 3
       0     .04   220.2    .035   262.4     .04
BR U Banks=220.2,
BR D #Sta/Elev= 30
       0   626.4    10.8  625.98    45.5  625.57   118.4  625.81   135.4  626.33
   163.4  626.24   182.4  624.84   190.4  623.62   202.4  619.29   203.7  618.52
   205.7  616.34   206.4  615.92   214.1 615.878   220.8  615.57   233.4  609.56
   236.3  608.79   242.3  607.91   245.4  607.94   251.7  608.77   256.4  609.86
   262.4  610.72   268.4  613.34   276.3  615.66   289.4  620.83   291.4  621.29
   293.4  622.43   302.4  624.31   320.4  624.67   324.4  624.41   405.1  627.75
BR D #Mann= 4
       0     .04   214.1    .035   220.8    .035   276.3     .04
BR D Banks=220.8,
BC Design=,, 0 ,, 0 ,,,,,,
BC Use User HTab Curves=0
BC User HTab FreeFlow(D)= 0

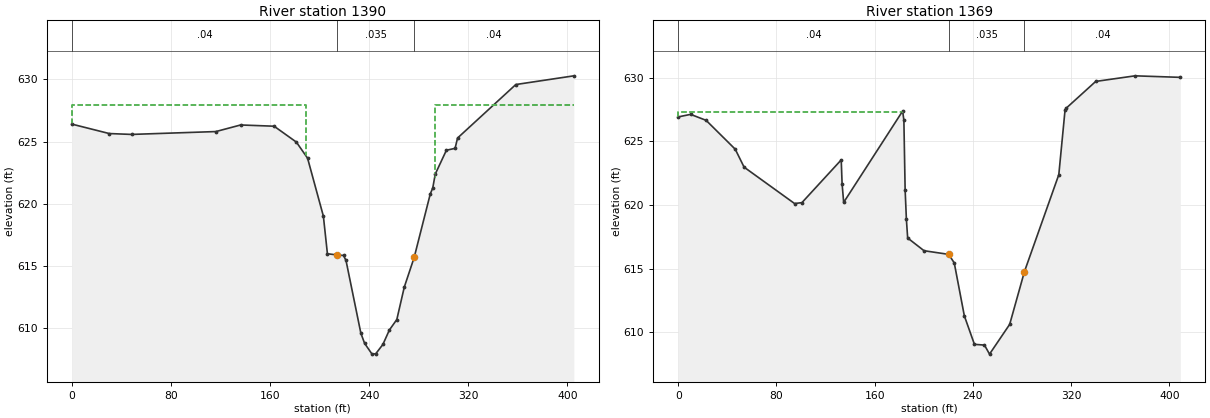
Type RM Length L Ch R = 1 ,1390    ,35.9,20.3,5
XS GIS Cut Line= 2
1644195.28169461 747654.37686746 1644203.4577824747249.310886466
#Sta/Elev= 30
       0   626.4   30.25  625.64   48.26  625.57  116.27   625.8  136.27  626.33
  163.28  626.23  181.28  624.95  190.28  623.66  203.04     619  206.29  615.98
   214.1  615.88  219.29  615.84  221.29  615.44  233.29  609.59  236.29  608.78
   242.3  607.91   245.3  607.94  251.08  608.69   256.3  609.85   262.3  610.69
   268.3  613.29   276.3  615.68  289.31  620.79  291.31  621.27  293.31  622.38
  302.31   624.3  309.31  624.45  311.31  625.28  358.32  629.58  405.15  630.28
#Mann= 3 ,0,0
       0     .04       0   214.1    .035       0   276.3     .04       0
#XS Ineff= 2 , 0
          189.06 627.975  292.72         627.975
Permanent Ineff=
       F       F
Bank Sta=214.1,276.3
XS Rating Curve= 0 ,0
Exp/Cntr(USF)=0,0
Exp/Cntr=0.5,0.3

Type RM Length L Ch R = 1 ,1369    ,48.5,50.5,48.5
XS GIS Cut Line= 4
  1644229.449022747654.8357411031644234.90336205747471.586406465
1644206.01334914747345.7762509351644208.88610736747249.260260605
#Sta/Elev= 30
       0  626.93   10.09  627.13   22.71  626.66   46.43  624.39   53.65  622.98
   94.75  620.12  100.75  620.19  132.76  623.55  133.47  621.68  134.76  620.21
  182.79  627.39   183.8  626.67  184.82   621.2  185.85  618.87  186.88  617.41
  200.21  616.41   220.3 616.123  224.84  615.45  233.05  611.29  241.26  609.05
  249.46  608.99  253.57  608.28  269.98  610.62     282 614.766     310  622.39
  315.06  627.45  316.06  627.62  340.07  629.72  372.09  630.16  408.97  630.04
#Mann= 3 ,0,0
       0     .04       0   220.3    .035       0     282     .04       0
#XS Ineff= 2 , 0
          183.04  627.28  315.77          627.28
Permanent Ineff=
       F       F
Bank Sta=220.3,282
XS Rating Curve= 0 ,0
Exp/Cntr(USF)=0,0
Exp/Cntr=0.5,0.3