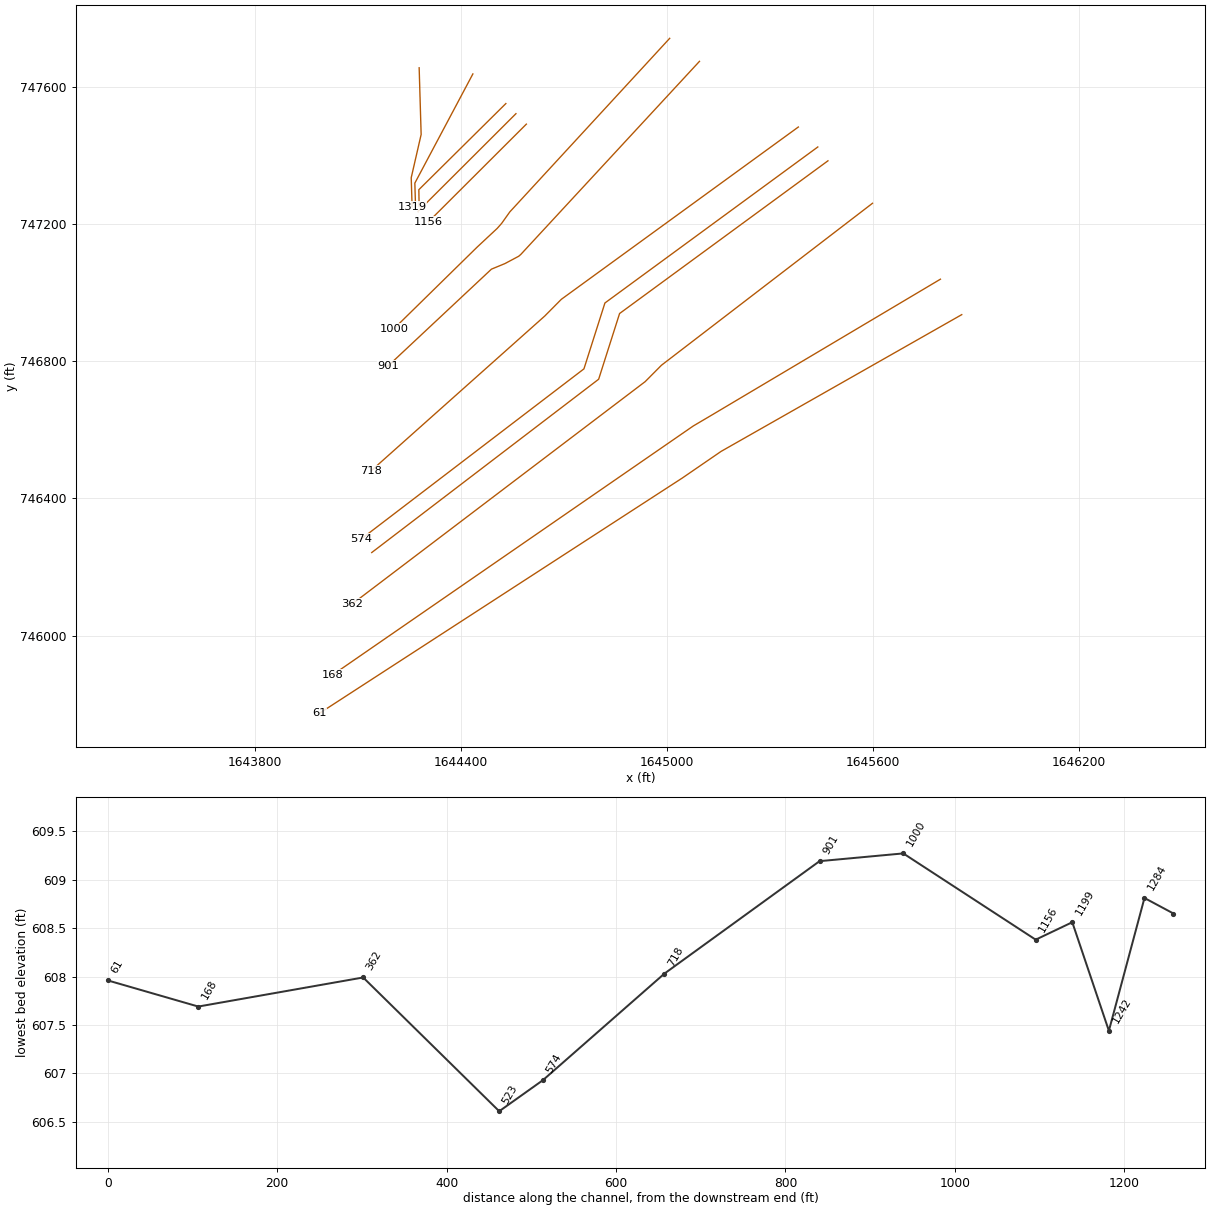
HEC-RAS study 105889_LUC23.prj: 105889_LUC-23

--- 105889_LUC23.g01 (geometry) --- (continued)

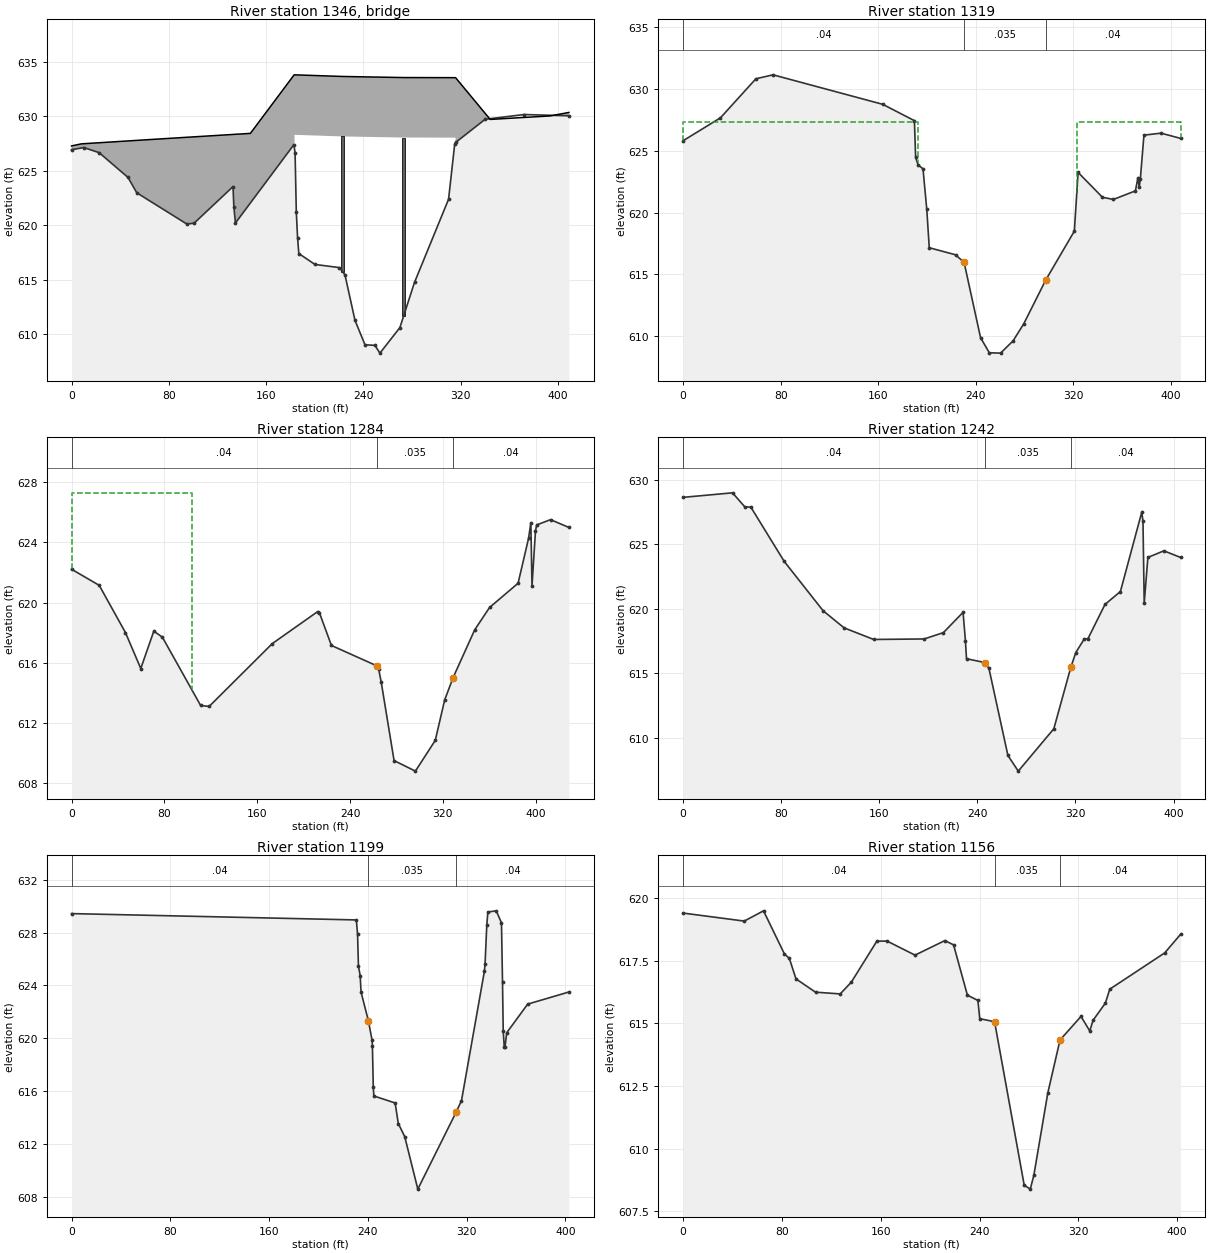
Type RM Length L Ch R = 3 ,1346    ,,,
BEGIN DESCRIPTION:
NP Ramp Proposed Bridge
END DESCRIPTION:
Bridge Culvert--1,0,-1,-1, 0
Deck Dist Width WeirC Skew NumUp NumDn MinLoCord MaxHiCord MaxSubmerge Is_Ogee
9.200634,28.33,2.6,0, 14, 14, , , 0.98, 0, 0,0,,
       0    8.06   53.72  100.07  147.04  183.04  183.34  222.74     273  315.77
  315.77  344.23  393.46  408.99
  627.28  627.47  627.79  628.11  628.43   633.8   633.8  633.65  633.55  633.54
  633.54  629.71  630.03  630.35
                                                   628.3  628.15  628.05  628.04
                                
       0    8.06   53.72  100.07  147.04  192.33  192.33  234.36  283.64  322.91
  322.91  344.23  393.46  408.99
  627.28  627.47  627.79  628.11  628.43  632.52  632.52  632.36  632.26  632.25
  632.25  629.71  630.03  630.35
                                                  627.02  626.86  626.76  626.75
                                
Pier Skew, UpSta & Num, DnSta & Num=  ,222.74, 2 ,234.36, 2 , 0 , 0 , 0 ,,
       2       2
       0  628.21
       2       2
       0   626.9
Pier Skew, UpSta & Num, DnSta & Num=  ,273, 2 ,283.64, 2 , 0 , 0 , 0 ,,
       2       2
       0  628.53
       2       2
       0  626.98
BR Coef=-1 , 0 , 0 ,, 0 ,,,0.8,-1,,0,
WSPro=,,,, 1 ,,,, 0 ,,,, 0 ,,,,-1 ,-1 ,-1 , 0 , 0 , 0 , 0 , 0
BR U #Sta/Elev= 30
       0  626.93   10.09  627.13   22.71  626.66   46.43  624.39   53.65  622.98
   94.75  620.12  100.75  620.19  132.76  623.55  133.47  621.68  134.76  620.21
  182.79  627.39   183.8  626.67  184.82   621.2  185.85  618.87  186.88  617.41
  200.21  616.41   220.3 616.123  224.84  615.45  233.05  611.29  241.26  609.05
  249.46  608.99  253.57  608.28  269.98  610.62     282 614.766     310  622.39
  315.06  627.45  316.06  627.62  340.07  629.72  372.09  630.16  408.97  630.04
BR U #Mann= 3
       0     .04   220.3    .035     282     .04
BR D #Sta/Elev= 30
       0   625.8   30.65  627.65   59.67   630.8   73.76  631.12  163.71  628.74
  189.72  627.42  190.72  624.46  192.72  623.85  196.78  623.53  199.86  620.26
  201.91  617.16  223.46  616.59   230.5  615.97  243.98   609.9  251.16  608.68
   260.4  608.65  270.66  609.64  279.38  611.01   297.5  614.56  320.93   618.5
     324  623.24  344.01  621.23  353.01  621.06  371.02  621.75  373.02  622.79
  374.14  622.07  375.02  622.67  378.02  626.25  392.03  626.41  408.04  625.99
BR D #Mann= 3
       0     .04   230.5    .035   297.5     .04
BC Design=,, 0 ,, 0 ,,,,,,
BC Use User HTab Curves=0
BC User HTab FreeFlow(D)= 0

Type RM Length L Ch R = 1 ,1319    ,66.7,34.2,10.1
XS GIS Cut Line= 4
1644277.84958058747654.7699379411644283.63503791 747460.39606385
  1644254.745025747334.5859083211644257.25893163747250.126246546
#Sta/Elev= 30
       0   625.8   30.65  627.65   59.67   630.8   73.76  631.12  163.71  628.74
  189.72  627.42  190.72  624.46  192.72  623.85  196.78  623.53  199.86  620.26
  201.91  617.16  223.46  616.59   230.5  615.97  243.98   609.9  251.16  608.68
   260.4  608.65  270.66  609.64  279.38  611.01   297.5  614.56  320.93   618.5
     324  623.24  344.01  621.23  353.01  621.06  371.02  621.75  373.02  622.79
  374.14  622.07  375.02  622.67  378.02  626.25  392.03  626.41  408.04  625.99
#Mann= 3 ,0,0
       0     .04       0   230.5    .035       0   297.5     .04       0
#XS Ineff= 2 , 0
          192.33  627.28  322.91          627.28
Permanent Ineff=
       F       F
Bank Sta=230.5,297.5
XS Rating Curve= 0 ,0
Exp/Cntr(USF)=0,0
Exp/Cntr=0.5,0.3

Type RM Length L Ch R = 1 ,1284    ,67.1,42,11.1
XS GIS Cut Line= 3
1644434.32225518747636.8136814361644265.27408015747318.689822915
1644267.30941485747250.308730678
#Sta/Elev= 30
       0  622.21   23.86  621.14    46.5     618   59.66  615.62    70.9   618.1
   78.29   617.7  111.23  613.17  118.55   613.1  172.95  617.27  212.14   619.4
  213.67  619.31  223.97  617.15     263 615.801  264.63   615.6   266.8  614.75
  277.95  609.51  296.33  608.81  313.45  610.85  321.58  613.54   328.8 615.013
  347.46  618.19  360.25  619.67  384.82  621.28  393.82  624.25  395.82  625.29
  396.82  621.11  399.83  624.75  400.83  625.15  412.83   625.5  428.66  624.98
#Mann= 3 ,0,0
       0     .04       0     263    .035       0   328.8     .04       0
#XS Ineff= 2 , 0
           104.1  627.28
Permanent Ineff=
       F       F
Bank Sta=263,328.8
XS Rating Curve= 0 ,0
Exp/Cntr(USF)=0,0
Exp/Cntr=0.3,0.1

Type RM Length L Ch R = 1 ,1242    ,42.4,43.2,47.3
XS GIS Cut Line= 3
 1644530.4010904747550.4860056451644276.91907605747299.548935233
1644277.80965665747250.499380966
#Sta/Elev= 30
       0  628.63    40.3  628.98   50.25   627.9   55.26  627.87   82.47  623.67
  114.22  619.85  131.27  618.53  155.44  617.63  196.66  617.67  212.29  618.16
  228.34  619.73  230.26  617.55  231.15  616.14     246 615.846  249.45  615.39
  264.93  608.65  273.37  607.44  302.38  610.72   316.2 615.465  320.32  616.62
  327.13  617.66  330.27   617.7   344.1  620.34  356.68  621.34   374.1  627.48
   375.1  626.79   376.1  620.44   379.1  623.98  392.11  624.49  405.74  623.98
#Mann= 3 ,0,0
       0     .04       0     246    .035       0   316.2     .04       0
Bank Sta=246,316.2
XS Rating Curve= 0 ,0
Exp/Cntr(USF)=0,0
Exp/Cntr=0.3,0.1

Type RM Length L Ch R = 1 ,1199    ,43.2,43.2,43.2
XS GIS Cut Line= 2
1644559.78421315747521.0384506371644274.64334717747236.535692051
#Sta/Elev= 30
       0  629.44  230.64  628.96  231.62  627.86  232.33  625.48  233.74  624.72
  234.45  623.49   240.4 621.311  243.39  619.83  243.64  619.42  244.35  616.29
   244.8  615.62  262.03  615.09  264.62  613.53  269.81  612.54  280.41  608.56
   311.4 614.388  315.77  615.26  334.31  625.06  334.86  625.61  336.27  628.56
  337.13  629.56  343.91  629.65  348.16  628.74     349  624.26  349.57  620.54
  350.42  619.32  350.99  619.32   352.4  620.41  369.39  622.58   402.8   623.5
#Mann= 3 ,0,0
       0     .04       0   240.4    .035       0   311.4     .04       0
Bank Sta=240.4,311.4
XS Rating Curve= 0 ,0
Exp/Cntr(USF)=0,0
Exp/Cntr=0.3,0.1

Type RM Length L Ch R = 1 ,1156    ,144.7,156.3,155
XS GIS Cut Line= 3
1644590.15617584 747490.599837831644397.08196246747297.957698904
1644305.01530986747206.097079244
#Sta/Elev= 30
       0  619.41    49.5  619.09    65.1   619.5      82  617.78      86   617.6
    91.4  616.78   107.2  616.25   127.2  616.18   136.2  616.65   156.9  618.29
   165.2  618.29   187.8  617.73   211.9  618.31     219  618.14   230.2  616.13
   238.7  615.92   240.2  615.19   252.2  615.07   276.2  608.54   281.1  608.38
     284  608.93   295.3  612.22   305.2  614.34   322.2  615.28   329.3   614.7
     332  615.13   341.9  615.81   345.5  616.37     390  617.82   402.8  618.56
#Mann= 3 ,0,0
       0     .04       0   252.2    .035       0   305.2     .04       0
Bank Sta=252.2,305.2
XS Rating Curve= 0 ,0
Exp/Cntr=0.5,0.3

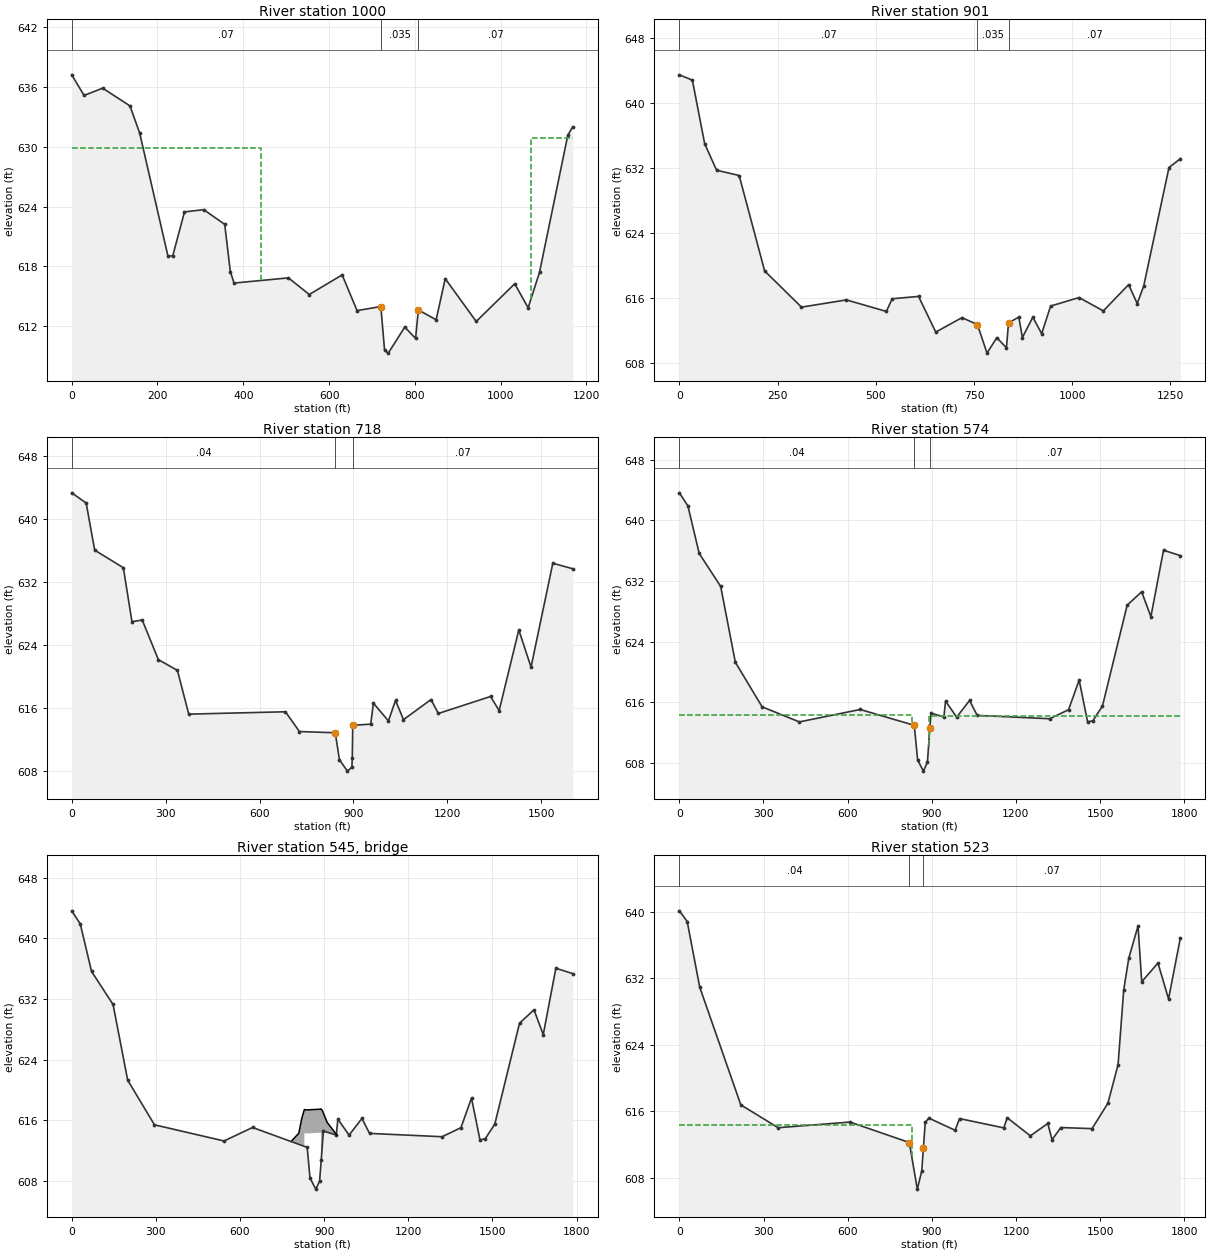
Type RM Length L Ch R = 1 ,1000    ,110.1,98.8,73.4
XS GIS Cut Line= 6
1645007.67995371747740.5112462211644541.89863589747234.824460543
1644518.22299249747201.5714440211644505.33223105747186.949334372
1644446.05820735747131.6398459121644203.94328587746894.114299887
#Sta/Elev= 30
       0  637.23   28.86  635.16   72.14  635.89  135.83  634.11  158.48  631.37
   224.3  619.03  235.51  619.04  262.91  623.46  307.83  623.68  356.72  622.21
  369.83  617.45  378.57  616.31  505.25  616.83  553.86  615.16  630.52  617.13
  665.34  613.54  720.71 613.953  729.42  609.56  738.08  609.27  776.54  611.89
   801.7  610.75   808.2 613.612  849.63  612.62  870.84  616.75  943.07  612.45
 1032.88  616.24 1064.16  613.82 1090.78  617.41 1156.64  631.16 1168.09  632.01
#Mann= 3 ,0,0
       0     .07       0  720.71    .035       0   808.2     .07       0
#XS Ineff= 2 , 0
          441.06  629.85 1070.82          630.85
Permanent Ineff=
       F       F
Bank Sta=720.71,808.2
XS Rating Curve= 0 ,0
Exp/Cntr=0.3,0.1

Type RM Length L Ch R = 1 ,901     ,202.7,183.1,200.4
XS GIS Cut Line= 6
1645094.46529865747673.4623152651644574.04884186747111.073063888
 1644567.8403802 747105.67714455 1644527.9411083747084.435736743
1644488.38327984747068.0602348411644186.97738589 746785.80866925
#Sta/Elev= 30
       0  643.44   33.13  642.79   64.45  634.96   94.79   631.7  152.25  631.05
  217.07  619.31  310.93  614.85  425.31  615.74  526.97  614.32  541.83  615.88
  608.96  616.17  652.72  611.78  719.49  613.56  758.88 612.696  783.21  609.19
  808.13  611.09  832.64  609.85     838 612.922  864.21  613.62  873.24  611.11
  899.84  613.61  922.37  611.58  945.05  614.98 1017.47  616.03 1079.31  614.39
  1143.7  617.62 1165.62  615.29 1182.06  617.44 1246.45  632.03 1275.42  633.12
#Mann= 3 ,0,0
       0     .07       0  758.88    .035       0     838     .07       0
Bank Sta=758.88,838
XS Rating Curve= 0 ,0
Exp/Cntr=0.3,0.1

Type RM Length L Ch R = 1 ,718     ,83.1,143.5,189.9
XS GIS Cut Line= 5
1645382.49403433747482.1788601071644692.15244325746980.344012146
1644675.58300697 746963.635705741644643.82821872746931.614777405
1644137.63003538746480.374743454
#Sta/Elev= 30
       0  643.33    46.2  642.03    73.4  636.06   164.9  633.83   192.4  626.99
   225.2   627.2   276.7  622.17   337.6  620.81   373.8  615.26   682.6  615.56
   727.4  613.05  841.72612.8973   855.1  609.47   880.5  608.03   894.8  608.53
   896.1  609.67   897.6  613.84   954.9  613.99   963.6  616.65  1011.6   614.4
  1034.2     617  1059.7  614.56  1147.6  617.11  1170.9  615.34  1337.8   617.5
  1365.2  615.71    1428  625.94    1467  621.22  1536.6   634.4  1600.2   633.7
#Mann= 3 ,0,0
       0     .04       0  841.72    .035       0   897.6     .07       0
#XS Ineff= 2 , 0
          690.33   614.3 1040.81          614.15
Permanent Ineff=
       F       F
Bank Sta=841.72,897.6
XS Rating Curve= 0 ,0
Exp/Cntr=0.5,0.3

Type RM Length L Ch R = 1 ,574     ,51.5,51.5,51.5
XS GIS Cut Line= 5
1645439.16444863747424.0189192761644819.01790981746969.551999535
1644789.21551792746875.9788162141644757.88656545746777.612556758
1644109.33935849746282.263577413
#Sta/Elev= 30
       0  643.63    30.4  641.91    70.7  635.64   147.4  631.28   199.6  621.29
   295.1  615.41   427.8  613.42   644.8  615.06   837.7  612.97   849.6   608.4
   870.1  606.93   884.6  608.13   893.2  612.66   897.4  614.59   943.2  614.06
   949.1  616.16   988.9  614.05  1034.8  616.25  1061.9  614.28  1320.5  613.84
  1387.8  615.03  1425.5  618.94  1455.7  613.42  1474.6  613.58  1508.6  615.51
  1596.7  628.81  1648.3  630.58  1681.3   627.3  1726.3  636.06  1786.4  635.35
#Mann= 3 ,0,0
       0     .04       0   837.7    .035       0   893.2     .07       0
#XS Ineff= 2 , 0
          829.55   614.3  888.59          614.15
Permanent Ineff=
       F       F
Bank Sta=837.7,893.2
XS Rating Curve= 0 ,0
Exp/Cntr=0.5,0.3

Type RM Length L Ch R = 3 ,545     ,,,
BEGIN DESCRIPTION:
Golf Cart Crossing
END DESCRIPTION:
Bridge Culvert--1,0,-1,-1, 0
Deck Dist Width WeirC Skew NumUp NumDn MinLoCord MaxHiCord MaxSubmerge Is_Ogee
23.39706,10.91,2.6,0, 13, 13, , , 0.98, 0, 0,0,,
  785.33  809.71  820.23  829.55  836.03  865.03  885.46  888.59  890.39  890.75
  894.89  910.54  945.08
  613.34   614.3  616.25  617.43  617.37  617.43  617.47  617.49  617.49  617.44
  617.19  615.74  614.08
                          614.33  614.27  614.33  614.37  614.39
                        
  785.33  809.71  820.23  829.55  836.03  865.03  885.46  888.59  890.39  890.75
  894.89  910.54  945.08
  613.34   614.3  616.25  617.43  617.37  617.43  617.47  617.49  617.49  617.44
  617.19  615.74  614.08
                          614.33  614.27  614.33  614.37  614.39
                        
BR Coef=-1 , 0 , 0 ,, 0 ,,,0.8,0,,0,
WSPro=,,,, 1 ,,,, 0 ,,,, 0 ,,,,-1 ,-1 ,-1 , 0 , 0 , 0 , 0 , 0
BR U #Sta/Elev= 30
       0  643.63    30.4  641.91    70.7  635.64   147.4  631.28   199.6  621.29
   295.1  615.41   543.1  613.28   644.8  615.06  839.59 612.433   849.6   608.4
   870.1  606.93   883.8  607.97  889.61 610.723   897.4  614.59   943.2  614.06
   949.1  616.16   988.9  614.05  1034.8  616.25  1061.9  614.28  1320.5  613.84
  1387.8  615.03  1425.5  618.94  1455.7  613.42  1474.6  613.58  1508.6  615.51
  1596.7  628.81  1648.3  630.58  1681.3   627.3  1726.3  636.06  1786.4  635.35
BR U #Mann= 3
       0     .04  839.59     .03  889.61     .07
BR D #Sta/Elev= 30
       0  640.14      28  638.85    72.5  630.95     219  616.76   352.2  614.01
   608.3  614.69  819.44 612.223   847.9  606.61   863.8  608.81  869.43 611.519
   874.1  613.79   908.1  615.22   982.7   613.7   998.4  615.11  1156.1  613.99
  1168.3  615.21  1250.7  613.03  1312.9  614.52    1328  612.56  1359.4  614.03
  1470.7   613.9  1527.1  616.96  1563.3   621.6  1583.4  630.59  1601.6  634.46
  1634.5  638.31  1647.6  631.59  1705.5  633.85  1743.2  629.53  1785.3  636.88
BR D #Mann= 3
       0     .04  819.44     .03  869.43     .07
BC Design=,, 0 ,, 0 ,,,,,,
BC Use User HTab Curves=0
BC User HTab FreeFlow(D)= 0

Type RM Length L Ch R = 1 ,523     ,196.8,160.6,93.5
XS GIS Cut Line= 5
1645468.71963841 747383.689144211644861.71530382746938.853330506
1644833.37375276746849.8668772311644800.74991045746747.434938595
1644139.68870537746242.527987014
#Sta/Elev= 30
       0  640.14      28  638.85    72.5  630.95     219  616.76   352.2  614.01
   608.3  614.69  819.44612.2231   847.9  606.61   863.8  608.81  869.43 611.519
   876.2  614.65   888.8  615.17   982.7   613.7   998.4  615.11  1156.1  613.99
  1168.3  615.21  1250.7  613.03  1312.9  614.52    1328  612.56  1359.4  614.03
  1470.7   613.9  1527.1  616.96  1563.3   621.6  1583.4  630.59  1601.6  634.46
  1634.5  638.31  1647.6  631.59  1705.5  633.85  1743.2  629.53  1785.3  636.88
#Mann= 3 ,0,0
       0     .04       0  819.44    .035       0  869.43     .07       0
#XS Ineff= 2 , 0
          829.55   614.3  888.59          614.15
Permanent Ineff=
       F       F
Bank Sta=819.44,869.43
XS Rating Curve= 0 ,0
Exp/Cntr=0.5,0.3

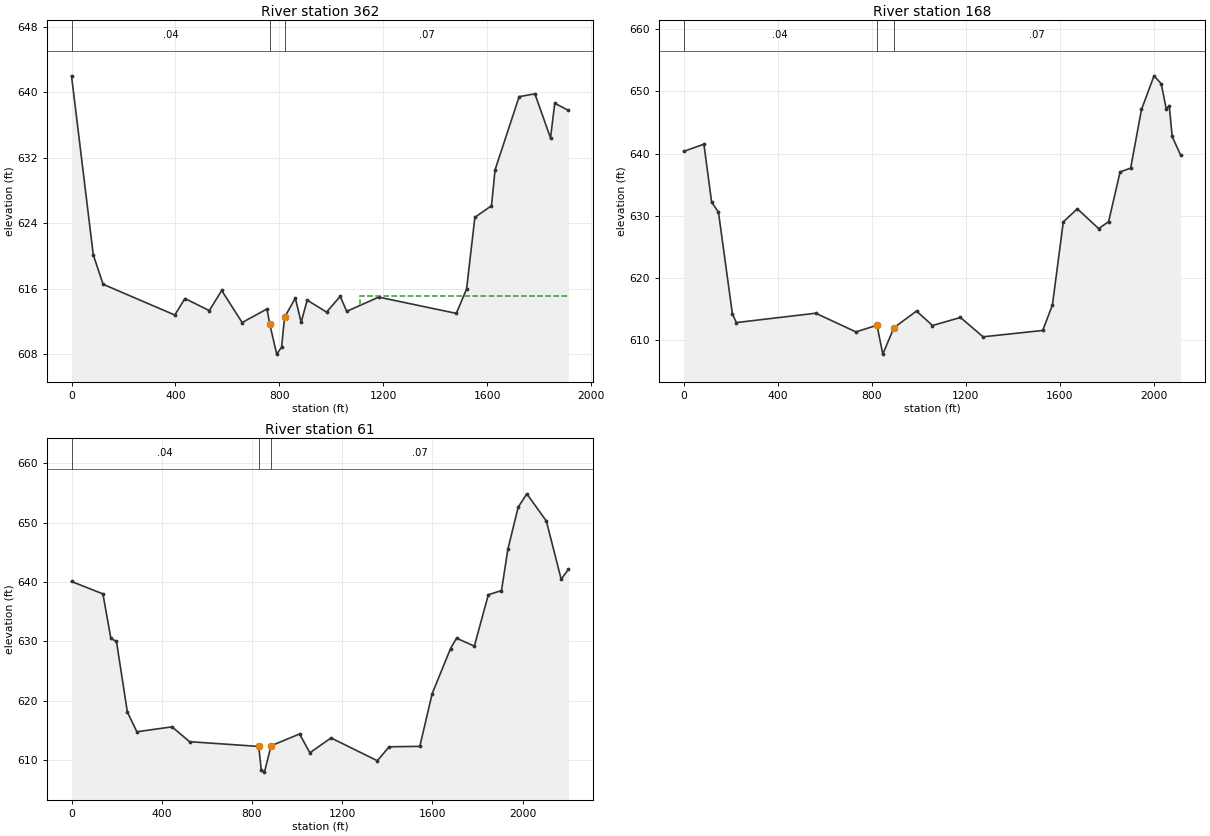
Type RM Length L Ch R = 1 ,362     ,217.3,194.6,178.9
XS GIS Cut Line= 5
1645598.55687532747260.0577567961644983.77783282746788.233144211
1644965.21489432746769.5456774191644936.37363163746740.510934957
1644083.20884319746093.027621414
#Sta/Elev= 30
       0  642.01    83.8  620.13   121.6  616.53   397.7  612.77   436.7  614.79
   530.6  613.31   578.2  615.77     657  611.85  752.66 613.511  763.47  611.64
  789.99  607.99  808.72  608.82  820.33  612.49  861.79 614.833   884.2  611.88
   907.5  614.59     982  613.13  1034.6  615.05  1059.7  613.22  1182.8  614.96
  1481.6  612.97  1521.2  615.95  1553.1  624.71  1617.1  626.13  1630.9  630.52
  1723.5  639.46  1784.1  639.81  1844.4  634.41  1860.7  638.66  1913.3  637.78
#Mann= 3 ,0,0
       0     .04       0  763.47    .035       0  820.33     .07       0
#XS Ineff= 2 , 0
          442.78   614.3 1112.12          615.15
Permanent Ineff=
       F       F
Bank Sta=763.47,820.33
XS Rating Curve= 0 ,0
Exp/Cntr=0.3,0.1

Type RM Length L Ch R = 1 ,168     ,107,107,107
XS GIS Cut Line= 6
1645796.39238367747038.8657238551645128.27864804746641.851994572
 1645102.4370471746626.6135624581645076.59544615746611.375130344
1645058.05278261746598.5775044461644025.26639986  745885.7773326
#Sta/Elev= 30
       0  640.34    86.2   641.5     119  632.16   148.1  630.56   207.3   614.2
   224.1  612.77   561.9  614.28   733.2  611.27  822.57612.3409   847.5  607.69
  894.47611.9343   990.9  614.63  1058.9   612.3    1178  613.59  1274.1  610.48
  1527.9   611.5  1569.2  615.59  1615.6  628.99  1675.3  631.09  1765.9  627.91
  1808.3  629.01  1857.2  637.03  1902.2  637.65  1948.3  647.09  2001.7  652.51
  2032.2  651.24  2054.1  647.11  2066.4  647.71  2078.9  642.74  2114.6  639.75
#Mann= 3 ,0,0
       0     .04       0  822.57    .035       0  894.47     .07       0
Bank Sta=822.57,894.47
XS Rating Curve= 0 ,0
Exp/Cntr=0.3,0.1

Type RM Length L Ch R = 1 ,61      ,,,
XS GIS Cut Line= 4
1645858.48672099746935.5751482211645157.53832781746537.258442256
1645044.05144511746459.3752874591643987.06577286745774.003525241
#Sta/Elev= 30
       0  640.08   139.3  637.99   174.5  630.49   199.4  629.98   247.7  618.08
   289.9  614.76   445.6  615.59   523.6  613.09   830.4  612.29   841.2  608.38
   855.6  607.96   885.1   612.4  1011.3  614.39    1057  611.22  1150.9  613.72
  1356.1  609.88  1408.6  612.23  1544.5   612.3  1599.3  621.17  1680.8  628.78
  1707.6  630.52  1786.4  629.19  1848.4  637.85  1906.8  638.55  1935.3  645.56
  1980.9  652.61  2019.2  654.85  2105.8  650.26  2171.4  640.472203.601  642.13
#Mann= 3 ,0,0
       0     .04       0   830.4    .035       0   885.1     .07       0
Bank Sta=830.4,885.1
XS Rating Curve= 0 ,0
Exp/Cntr(USF)=0,0
Exp/Cntr=0.3,0.1
LCMann Table=0

Chan Stop Cuts=-1
Use User Specified Reach Order=0
Composite Channel Slope=5

--- 105889_LUC23.g02 (geometry) ---

Geom Title=LUC-23_EX
Program Version=6.31

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
River Reach=Ottawa River    ,Reach
Reach XY= 30
      1643345.94       747695.821643394.32824547747678.525457639
1643531.86238861747619.0056671481643614.19335023 747560.94657253
 1643658.9510741747532.969104512      1643706.23747496.239872073
      1643788.62       747451.43      1643808.66       747437.81
      1643914.56       747404.66      1643929.86       747400.68
      1643976.97       747394.02      1644019.39       747407.14
       1644097.5       747411.65      1644122.04       747410.02
      1644193.88       747412.86      1644216.38       747405.72
       1644267.5       747399.78      1644346.28       747340.98
      1644435.09       747265.77      1644608.43       747020.06
       1644676.3       746963.04       1644808.1       746861.93
      1644944.16        746792.6      1644969.51       746745.54
      1644980.02       746711.27      1645019.87        746666.9
      1645042.81       746628.38      1645062.99       746588.93
      1645096.93       746539.39      1645147.54       746456.92

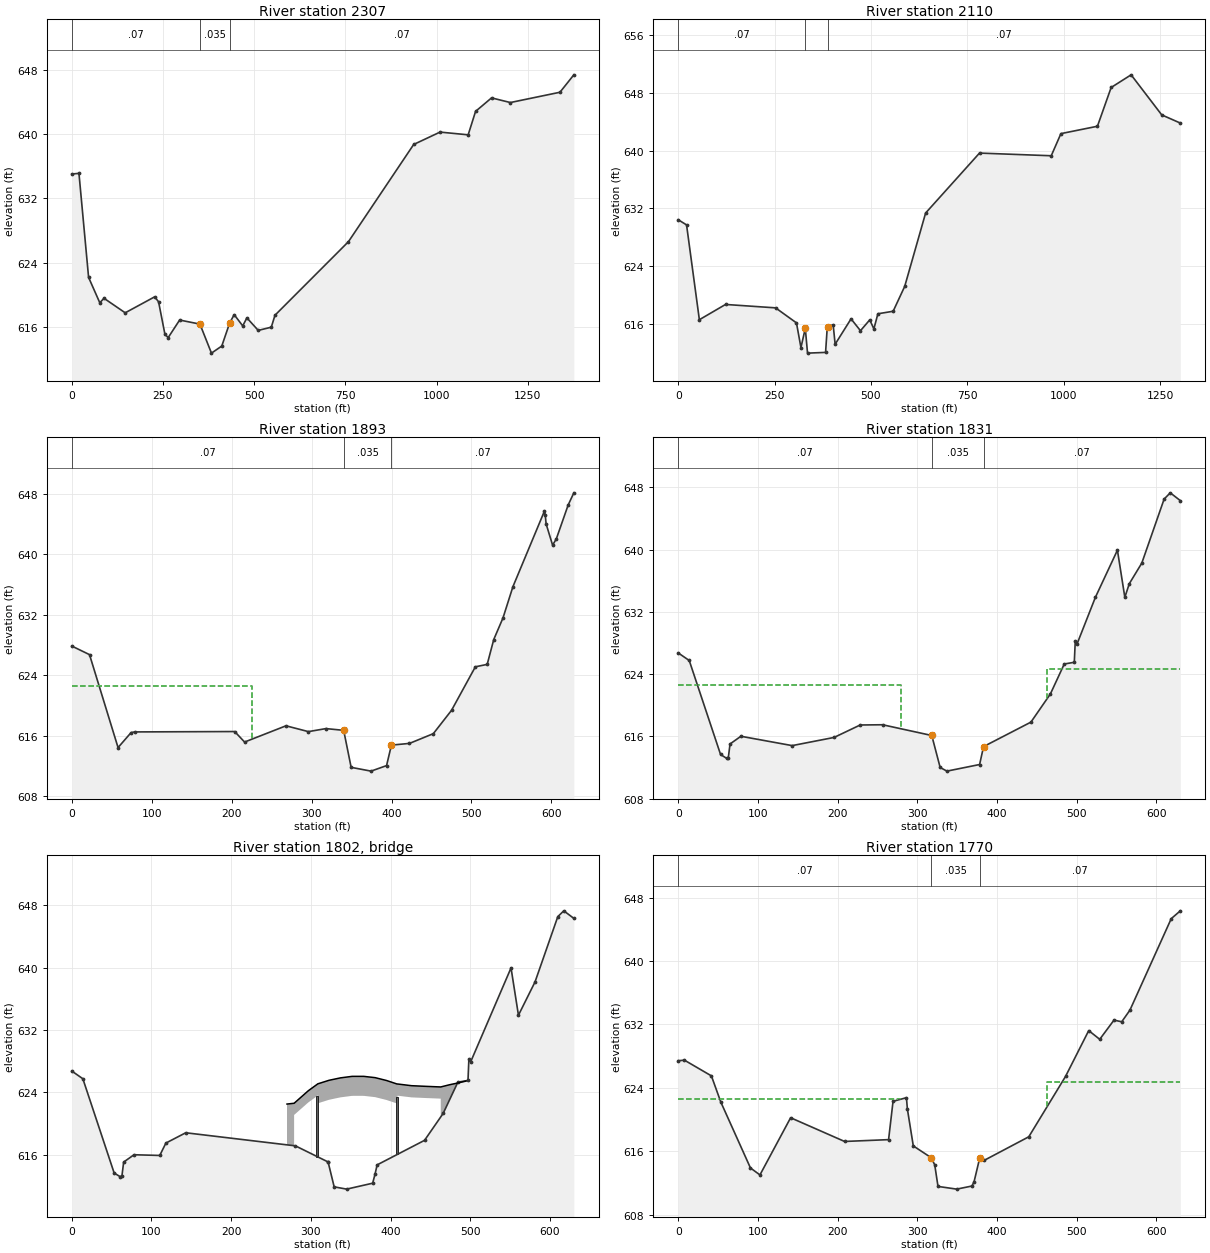
Type RM Length L Ch R = 1 ,2307    ,199.13,194.8,185.9
XS GIS Cut Line= 6
1643581.13075117748014.7312732611643401.75901531747773.626241877
1643289.41424645 747547.856432251643082.76194768747154.072091933
1643035.71829695747068.095764735 1642911.0769413746816.887948785
#Sta/Elev= 30
       0  635.03    19.7  635.11    46.1  622.16    76.8     619    88.3  619.56
   146.4  617.75   227.2  619.74   237.9  619.12   255.4  615.05   264.3  614.67
   295.6  616.85  351.25616.3442   382.8  612.73   411.1  613.61   432.7616.4847
   445.1  617.52   468.5  616.12   479.9  617.12     511  615.56   546.8  615.96
   556.9  617.45   758.3  626.61     937  638.71  1009.2  640.25  1086.3  639.91
  1106.6  642.83  1150.4  644.51  1201.9  643.93  1337.8  645.21  1375.9  647.38
#Mann= 3 ,0,0
       0     .07       0  351.25    .035       0   432.7     .07       0
Bank Sta=351.25,432.7
XS Rating Curve= 0 ,0
Exp/Cntr=0.3,0.1

Type RM Length L Ch R = 1 ,2110    ,213.75,220.7,210.7
XS GIS Cut Line= 6
1643743.54382237747910.7896994671643588.31002458747692.930452251
1643434.92529538747432.4483916751643308.78776383747214.233491164
1643248.70647299747094.0709094771643080.13554265746791.661712566
#Sta/Elev= 30
       0  630.43    21.6  629.72    54.8  616.61   122.7  618.72   252.5  618.25
   306.7  616.17   318.3  612.76  329.58 615.418   335.4  611.99   382.2  612.09
   386.5  615.51  388.74 615.651   401.9  615.91     407  613.22   448.3  616.73
   472.7  615.09   496.8  616.59   507.5  615.34   517.9  617.43   557.5  617.78
   587.5  621.22   641.7  631.36   781.5  639.65   967.6  639.28   992.7  642.34
  1087.4  643.36    1123  648.72  1174.8  650.47  1254.2  644.93  1302.4   643.8
#Mann= 3 ,0,0
       0     .07       0  329.58    .035       0  388.74     .07       0
Bank Sta=329.58,388.74
XS Rating Curve= 0 ,0
Exp/Cntr=0.3,0.1

Type RM Length L Ch R = 1 ,1893    ,74.58,61.8,46.7
XS GIS Cut Line= 4
1643892.34592037747816.9993893851643733.62045148747511.358742855
1643663.54337893747404.9867723521643586.48601673747268.992013356
#Sta/Elev= 30
       0  627.87    22.2  626.73    57.9  614.43    74.2  616.41    78.6   616.5
   203.8  616.55   216.2  615.16     268  617.31     296  616.54     318  616.94
  340.15  616.71   349.5  611.81   374.4  611.31   393.8  612.04  399.88 614.753
   422.5  614.98   452.3  616.27   475.1  619.36   504.9  625.12   519.7  625.44
   527.9  628.73   539.5   631.6   551.9  635.73   591.1  645.68   592.3  645.28
   593.4  644.04   601.5  641.23   606.1  642.03     621  646.54   628.1  648.15
#Mann= 3 ,0,0
       0     .07       0  340.15    .035       0  399.88     .07       0
#XS Ineff= 2 ,-1
       0  225.42 622.604  514.16 628.087  624.69
Permanent Ineff=
       F       F
Bank Sta=340.15,399.88
XS Rating Curve= 0 ,0
Exp/Cntr(USF)=0,0
Exp/Cntr=0.5,0.3

Type RM Length L Ch R = 1 ,1831    ,61.2,61.2,61.2
XS GIS Cut Line= 6
1643946.93118752 747761.929025931643820.59901614747517.330771878
1643798.69881424747487.1228856691643701.66442316747383.993529173
1643690.05410812747368.3274663981643612.90734924747232.528901836
#Sta/Elev= 30
       0  626.73    13.8  625.76    53.1  613.68    60.6  613.19    62.8  613.25
      65  615.03    78.6  616.02   142.9  614.82   195.5  615.87   228.3  617.47
   256.4   617.5  318.08  616.12   328.6  612.01   337.1  611.54   378.1  612.39
  383.04 614.693   442.5  617.84   466.9  621.46   484.3  625.31   496.9  625.53
   498.1  628.23   500.4   627.9   523.4  633.89     551  639.94   560.3  633.88
   565.9  635.63   581.6  638.28   609.6  646.51   617.3  647.31   629.9  646.31
#Mann= 3 ,0,0
       0     .07       0  318.08    .035       0  383.04     .07       0
#XS Ineff= 2 , 0
          278.96 622.604  462.93         624.697
Permanent Ineff=
       F       F
Bank Sta=318.08,383.04
XS Rating Curve= 0 ,0
Exp/Cntr=0.5,0.3

Type RM Length L Ch R = 3 ,1802    ,,,
BEGIN DESCRIPTION:
Pedestrian Bridge
END DESCRIPTION:
Bridge Culvert--1,0,-1,-1, 0
Deck Dist Width WeirC Skew NumUp NumDn MinLoCord MaxHiCord MaxSubmerge Is_Ogee
21.76832,13.5,2.6,0, 19, 19, , , 0.98, 0, 0,0,,
  270.03  278.96  296.75  308.95  309.28  322.84  337.08  351.69  366.27  380.61
  394.84  408.06  408.73  426.09  444.87  462.93  473.72  484.16  494.39
 622.504 622.604  624.21 625.116 625.116 625.554 625.862 626.056 626.056 625.891
 625.527 625.077 625.077  624.86 624.772 624.697 624.974 625.202 625.444
         621.104  622.71 623.616 622.616 623.054 623.362 623.556 623.556 623.391
 623.027 622.577 623.577  623.36 623.272 623.197
  270.03  278.96  296.75  308.95  309.28  322.84  337.08  351.69  366.27  380.61
  394.84  408.06  408.73  426.09  444.87  462.93  473.72  484.16  494.39
 622.504 622.604  624.21 625.116 625.116 625.554 625.862 626.056 626.056 625.891
 625.527 625.077 625.077  624.86 624.772 624.697 624.974 625.202 625.444
         621.104  622.71 623.616 622.616 623.054 623.362 623.556 623.556 623.391
 623.027 622.577 623.577  623.36 623.272 623.197
Pier Skew, UpSta & Num, DnSta & Num=  ,307.95, 2 ,307.95, 2 , 0 , 0 , 0 ,,
     2.5     2.5
       0 625.116
     2.5     2.5
       0 625.116
Pier Skew, UpSta & Num, DnSta & Num=  ,408.61, 2 ,408.61, 2 , 0 , 0 , 0 ,,
     2.5     2.5
       0 625.077
     2.5     2.5
       0 625.077
BR Coef=-1 , 0 , 0 ,, 0 ,,,0.8,0,,0,
WSPro=,,,, 1 ,,,, 0 ,,,, 0 ,,,,-1 ,-1 ,-1 , 0 , 0 , 0 , 0 , 0
BR U #Sta/Elev= 30
       0  626.74    13.9  625.75    53.2  613.65    60.7  613.19    62.9  613.26
    65.1  615.06    78.1     616   110.4  615.91   118.1   617.5     143  618.82
   280.6  617.14  321.25 615.091   321.6  615.07   329.2  611.88   344.9  611.59
   377.5  612.35  380.45 613.498   383.1   614.7   442.6  617.85     466  621.31
   484.4  625.31   497.1  625.53   498.2  628.23   500.5  627.93   551.1  639.97
   560.4   633.9   581.2  638.17   609.8  646.55   617.3  647.29   629.9  646.32
BR U #Mann= 3
       0     .07  321.25     .03  380.45     .04
BR U Banks=321.6,383.1
BR D #Sta/Elev= 30
       0  627.43     8.5  627.45    41.7   625.5    53.5   622.2    90.7  613.88
   102.6  613.02   141.1  620.39   286.4  622.76   313.4  616.77     315   615.3
  317.47 615.145   327.6  611.56   349.3  611.02   369.9  611.93  376.05 614.348
   378.1  615.14   419.3  616.65   431.4  617.89   438.6  617.98   495.5  626.87
   515.1  631.28   516.2  630.81   521.7     631   528.9  630.12   546.8  632.54
   556.5  632.36   567.4  633.96   578.2  636.72   618.6  645.36   629.9  646.31
BR D #Mann= 3
       0     .07  317.47     .03  376.05     .04
BC Design=,, 0 ,, 0 ,,,,,,
BC Use User HTab Curves=0
BC User HTab FreeFlow(D)= 0

Type RM Length L Ch R = 1 ,1770    ,16.8,48,117.7
XS GIS Cut Line= 6
1643998.70128398 747731.60062104 1643872.3691126747487.002366987
 1643850.4689107747456.7944807791643753.43451962747353.665124283
1643741.82420458747337.999061507 1643664.6774457747202.200496946
#Sta/Elev= 30
       0  627.42     7.8  627.49    41.6  625.51    53.4  622.21    90.6   613.9
   102.5  613.02     141  620.23   208.7  617.24   263.9  617.47   269.5   622.3
   286.3  622.76   287.5  621.32   294.9  616.68  317.47615.1855   321.8  614.29
   325.9  611.57   349.4  611.23   368.4  611.62   371.1  612.14   378.1615.1011
   384.1  614.87   439.8  617.83   485.9  625.44     515  631.22   528.8  630.12
   546.7  632.54   556.4  632.33   566.7   633.8   618.5  645.33   629.9  646.32
#Mann= 3 ,0,0
       0     .07       0  317.47    .035       0   378.1     .07       0
#XS Ineff= 2 , 0
          278.96 622.604  462.93         624.697
Permanent Ineff=
       F       F
Bank Sta=317.47,378.1
XS Rating Curve= 0 ,0
Exp/Cntr=0.5,0.3

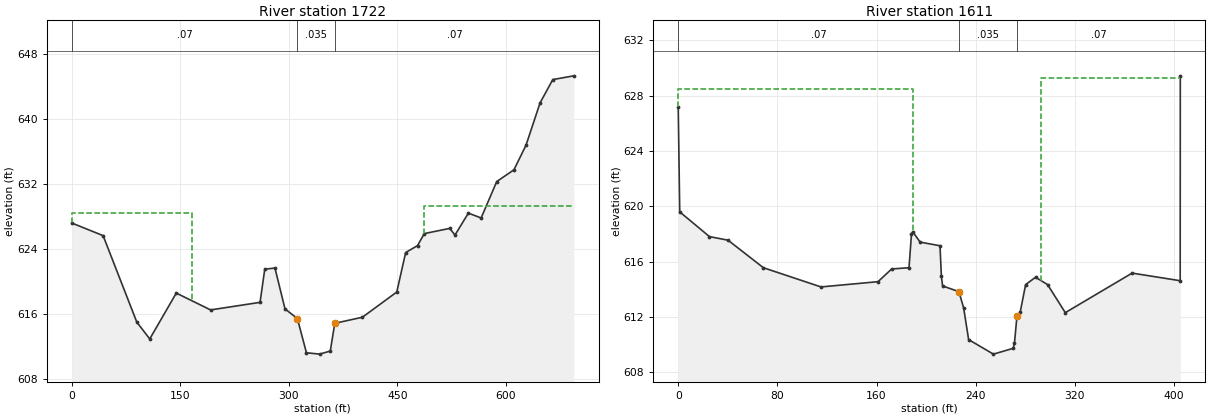
Type RM Length L Ch R = 1 ,1722    ,88.96,111.3,136.56
XS GIS Cut Line= 4
1644003.38275671 747727.722517171643962.44911272747650.365235112
1643885.93477143747468.3930929371643784.97464554747071.821027881
#Sta/Elev= 30
       0  627.22    43.3  625.67    89.9  615.03   107.8  612.96   144.5   618.6
   191.9  616.53   260.3  617.46   266.8  621.54   280.9  621.68   294.8  616.65
   311.9 615.464   324.4  611.26   342.6  611.09   357.4  611.47  363.62 614.881
   401.8  615.63   449.3  618.73   461.6  623.59     478  624.44   487.4  625.92
   522.5  626.56   529.8  625.74   548.3  628.44   565.9  627.84   587.5  632.32
   611.3  633.77     628   636.8   647.4     642     665  644.87   694.1  645.33
#Mann= 3 ,0,0
       0     .07       0   311.9    .035       0  363.62     .07       0
#XS Ineff= 2 , 0
          165.97  628.51   487.3          629.27
Permanent Ineff=
       F       F
Bank Sta=311.9,363.62
XS Rating Curve= 0 ,0
Exp/Cntr(USF)=0,0
Exp/Cntr=0.3,0.1

Type RM Length L Ch R = 1 ,1611    ,253.1,253.1,253.1
XS GIS Cut Line= 3
1643976.42280911 747650.240208161643981.04555429747395.638220761
1643983.77776243747245.159318031
#Sta/Elev= 30
       0  627.16     1.2   619.6    25.2  617.81    40.2  617.55    68.7  615.56
   115.2  614.17   161.2  614.55   172.2  615.47   186.2  615.56   188.2     618
   189.2  618.16   195.2  617.41   211.2  617.15   212.3  614.98   213.3  614.24
  226.48613.8315   230.3  612.64   234.3  610.36   254.3  609.31   270.3  609.73
   271.3  610.11   273.3  612.06   275.9  612.34   280.3  614.34   288.3  614.87
     298  614.34   312.3  612.31   366.2  615.17     405  614.62   405.1  629.44
#Mann= 3 ,0,0
       0     .07       0  226.48    .035       0   273.3     .07       0
#XS Ineff= 2 , 0
          189.26  628.51  292.92          629.27
Permanent Ineff=
       F       F
Bank Sta=226.48,273.3
XS Rating Curve= 0 ,0
Exp/Cntr=0.5,0.3