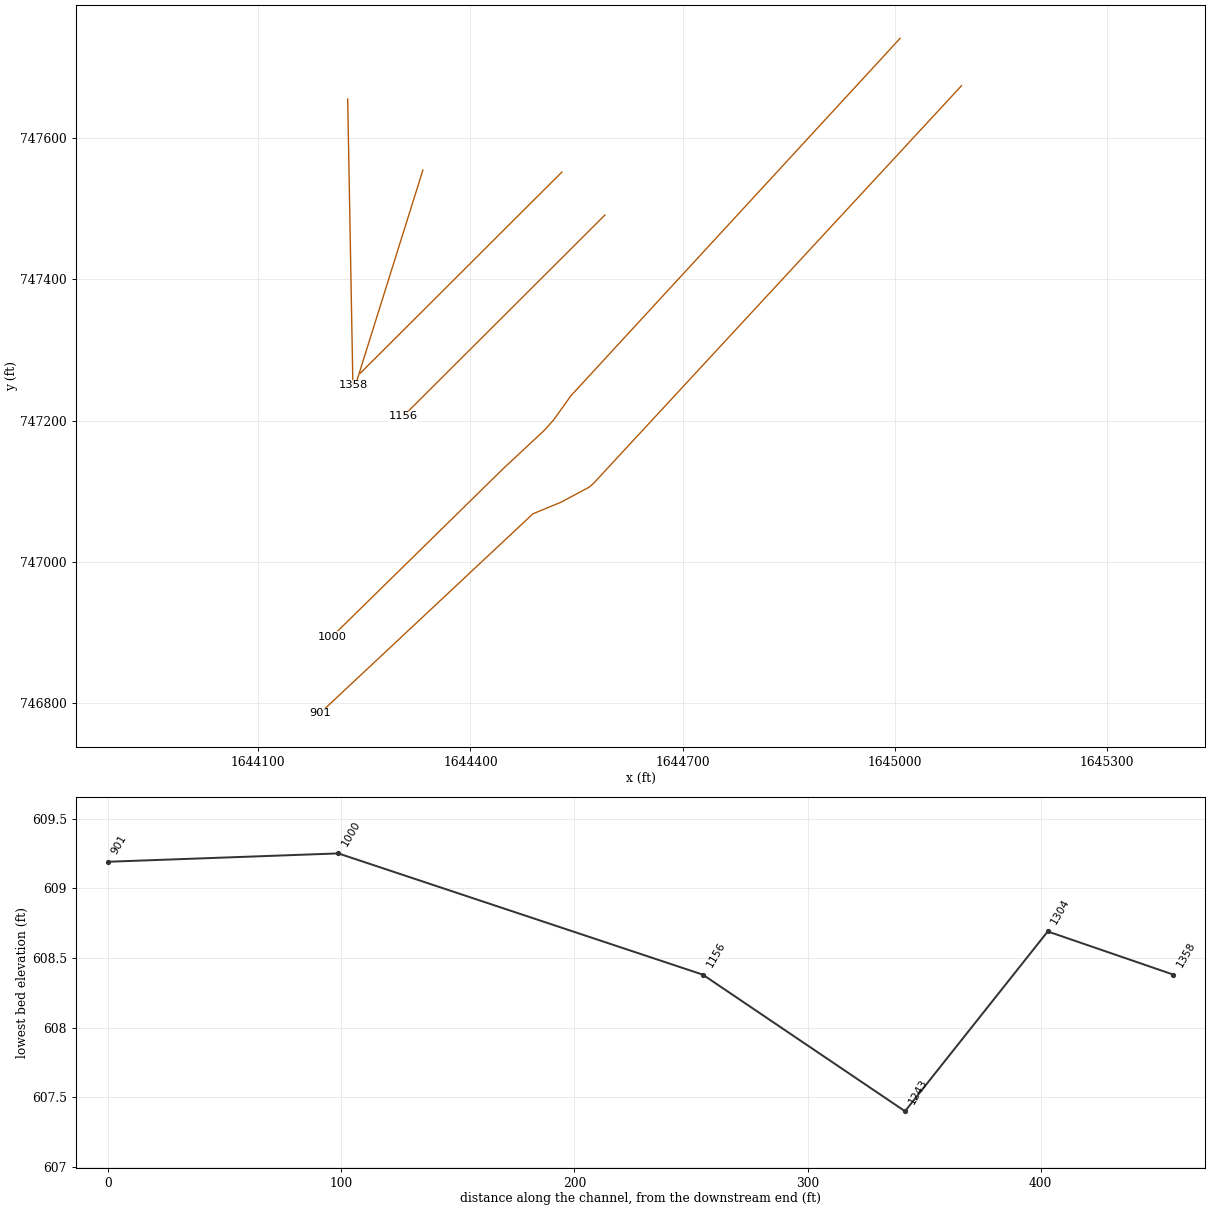
HEC-RAS study 105889_LUC23.prj: 105889_LUC-23

--- 105889_LUC23.g02 (geometry) --- (continued)

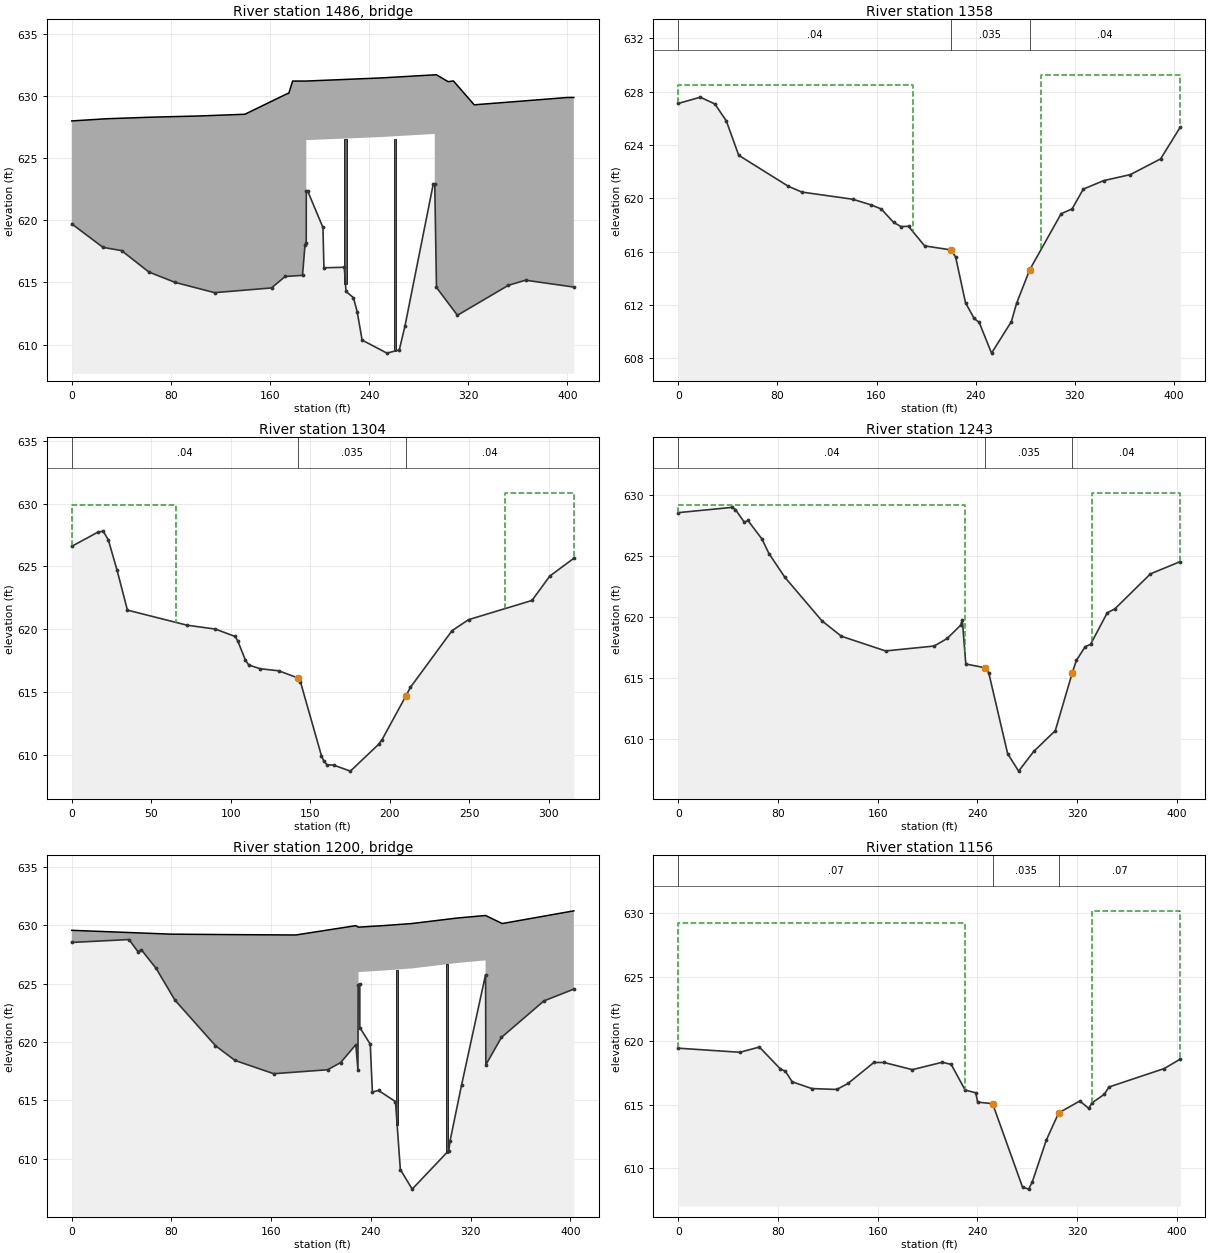
Type RM Length L Ch R = 3 ,1486    ,,,
BEGIN DESCRIPTION:
SB & NB Twin Bridges US-23
END DESCRIPTION:
Bridge Culvert--1,0,-1,-1, 0
Deck Dist Width WeirC Skew NumUp NumDn MinLoCord MaxHiCord MaxSubmerge Is_Ogee
38.30949,173.23,2.6,0, 18, 18, , , 0.98, 0, 0,0,,
       0   28.07   65.48  101.94  139.69  174.16  175.11  178.21  189.26  249.55
  292.92  294.28  303.72  307.97  324.73  363.29  399.95  405.15
 627.975  628.15  628.28  628.37  628.51  630.18  630.19  631.18  631.18  631.43
  631.68  631.68  631.13  631.19  629.27  629.57  629.86  629.86
                                                                  626.43  626.68
  626.93
       0   28.07   65.48  101.94  139.69  174.16  175.11  178.21  189.26  249.55
  292.92  294.28  303.72  307.97  324.73  363.29  399.95  405.15
 627.975  628.15  628.28  628.37  628.51  630.18  630.19  631.18  631.18  631.43
  631.68  631.68  631.13  631.19  629.27  629.57  629.86  629.86
                                                                  626.43  626.68
  626.93
Pier Skew, UpSta & Num, DnSta & Num=  ,220.9, 2 ,220.9, 2 , 0 , 0 , 0 ,,
       2       2
       0   626.5
       2       2
       0   626.5
Pier Skew, UpSta & Num, DnSta & Num=  ,260.94, 2 ,260.94, 2 , 0 , 0 , 0 ,260.94,260.94
       2       2
       0   626.5
       2       2
       0   626.5
BR Coef=-1 , 0 , 0 ,, 0 ,,,0.8,-1,,0,
WSPro=,,,, 1 ,,,, 0 ,,,, 0 ,,,,-1 ,-1 ,-1 , 0 , 0 , 0 , 0 , 0
BR U #Sta/Elev= 30
       0   619.7    25.2  617.81    40.2  617.55    62.2  615.83    83.2     615
   115.2  614.17   161.2  614.55   172.2  615.47   186.2  615.56   188.2     618
   189.2  618.16  189.26  622.35  190.31  622.35  202.69  619.41  203.47  616.17
  219.92  616.21   221.3  614.27   227.3  613.77   230.3  612.64   234.3  610.36
   254.3  609.31   264.3  609.57   268.9   611.5   291.7   622.9  292.92   622.9
   294.3  614.59   311.2  612.35   352.3  614.76   366.2  615.17   405.1  614.62
BR U #Mann= 3
       0    .012   227.3     .03   268.9     .04
BR U Banks=227.3,268.9
BR D #Sta/Elev= 30
       0  627.12    17.8  627.59    29.6  627.08    38.8  625.81    48.8  623.23
    88.9   620.9   155.8   619.5   179.8  617.88   187.8  617.73  189.26  622.74
  190.05  622.74  202.12  619.35  203.13  615.92  219.44  615.69   219.5  616.16
   219.8  616.16   223.8   615.6   231.8  612.16   242.8  610.69   252.8  608.38
   263.7  609.96  267.92   611.5  291.44  623.26  292.92  623.26   293.2  616.21
   308.9  618.84   317.8  619.21   326.8  620.69   389.2  622.96   405.1  625.35
BR D #Mann= 3
       0    .012   223.8     .03  292.92     .04
BR D Banks=223.8,267.92
BC Design=,, 0 ,, 0 ,,,,,,
BC Use User HTab Curves=0
BC User HTab FreeFlow(D)= 0

Type RM Length L Ch R = 1 ,1358    ,76.2,53.9,29.5
XS GIS Cut Line= 3
1644226.38142395747654.7800434851644230.94045178747403.687348174
1644233.73637727747249.699153356
#Sta/Elev= 30
       0  627.12    17.8  627.59    29.6  627.08    38.8  625.81    48.8  623.23
    88.9   620.9    99.7  620.47   140.9  619.93   155.8   619.5   163.8   619.2
   173.8  618.19   179.8  617.88   185.8   617.9   198.8  616.43     220616.1285
   223.8   615.6   231.8  612.16   238.8  610.98   242.8  610.69   252.8  608.38
   268.8  610.75     273  612.12   283.6  614.64   308.9  618.84   317.8  619.21
   326.8  620.69   343.3  621.33   364.8  621.78   389.2  622.96   405.1  625.35
#Mann= 3 ,0,0
       0     .04       0     220    .035       0   283.6     .04       0
#XS Ineff= 2 , 0
          189.26  628.51  292.92          629.27
Permanent Ineff=
       F       F
Bank Sta=220,283.6
XS Rating Curve= 0 ,0
Exp/Cntr=0.5,0.3

Type RM Length L Ch R = 1 ,1304    ,96.8,61.2,37.1
XS GIS Cut Line= 2
1644332.73334953747554.2029325911644238.28494176747252.928894511
#Sta/Elev= 30
       0  626.59    16.6  627.73    19.8  627.79      23   627.1    28.5  624.68
      35  621.51    72.5  620.31    90.3     620   102.8  619.41   104.4  619.05
   109.2  617.53   111.3  617.14   118.6  616.84   130.1  616.68  142.21 616.113
   143.8   615.8     157  609.92   158.4  609.52   160.5  609.19   164.7  609.17
   175.2  608.69     193  610.83   195.1  611.19  210.04 614.659   212.9  615.35
   239.1  619.87   249.5  620.75   289.4  622.28   300.6  624.22 315.732  625.64
#Mann= 3 ,0,0
       0     .04       0  142.21    .035       0  210.04     .04       0
#XS Ineff= 2 , 0
           65.81  629.85   272.2          630.85
Permanent Ineff=
       F       F
Bank Sta=142.21,210.04
XS Rating Curve= 0 ,0
Exp/Cntr(USF)=0,0
Exp/Cntr=0.5,0.3

Type RM Length L Ch R = 1 ,1243    ,86.7,86.7,86.7
XS GIS Cut Line= 3
1644529.41225045747551.4770634451644329.68271539747352.194496559
1644244.27138448747266.974304859
#Sta/Elev= 30
       0  628.54    43.1  628.97    45.9  628.79      53  627.76    55.9   627.9
    67.2  626.38    72.8  625.19    85.4  623.27   115.3  619.69   130.9  618.43
   166.3  617.23   205.3  617.63   215.8  618.25   226.5  619.33   227.9  619.78
   230.7  616.16  246.11 615.856   249.1  615.44   264.3  608.82   273.1   607.4
   285.2  609.01   302.5  610.71   316.2615.4642   319.4  616.45   326.5  617.58
   330.8  617.77   344.2  620.35   350.3  620.67   378.8  623.53   402.8  624.54
#Mann= 3 ,0,0
       0     .04       0  246.11    .035       0   316.2     .04       0
#XS Ineff= 2 , 0
          230.04  629.18  331.98          630.16
Permanent Ineff=
       F       F
Bank Sta=246.11,316.2
XS Rating Curve= 0 ,0
Exp/Cntr=0.5,0.3

Type RM Length L Ch R = 3 ,1200    ,,,
BEGIN DESCRIPTION:
NB Off Ramp Bridge
END DESCRIPTION:
Bridge Culvert--1,0,-1,-1, 0
Deck Dist Width WeirC Skew NumUp NumDn MinLoCord MaxHiCord MaxSubmerge Is_Ogee
26.10526,33.91,2.6,0, 12, 12, , , 0.98, 0, 0,0,,
       0   79.92   129.6  179.74  227.86  230.04  252.25  272.71     309  331.98
  345.35   402.8
  629.58  629.25  629.21  629.18  629.98  629.85     630  630.16  630.63  630.85
  630.16  631.25
                                             626  626.15  626.31  626.78     627
                
       0   79.92   129.6  179.74  227.86  230.04  252.25  272.71     309  331.98
  345.35   402.8
  629.58  629.25  629.21  629.18  629.98  629.85     630  630.16  630.63  630.85
  630.16  631.25
                                             626  626.15  626.31  626.78     627
                
Pier Skew, UpSta & Num, DnSta & Num=  ,261.04, 2 ,261.04, 2 , 0 , 0 , 0 ,,
       2       2
       0   626.5
       2       2
       0   626.5
Pier Skew, UpSta & Num, DnSta & Num=  ,300.98, 2 ,300.98, 2 , 0 , 0 , 0 ,,
       2       2
       0     627
       2       2
       0     627
BR Coef=-1 , 0 , 0 ,, 0 ,,,0.8,-1,,0,
WSPro=,,,, 1 ,,,, 0 ,,,, 0 ,,,,-1 ,-1 ,-1 , 0 , 0 , 0 , 0 , 0
BR U #Sta/Elev= 30
       0  628.54    45.9  628.79      53  627.76    55.9   627.9    67.7  626.31
    82.8  623.59   115.3  619.69   130.9  618.43     162  617.29   205.3  617.63
   215.8  618.25   227.9  619.78   229.6   617.6  229.75 624.922  231.08  624.95
   231.1  621.25  239.46  619.82  241.17  615.72  246.11 615.856  259.71   614.9
   263.6  609.08   273.1   607.4   302.5  610.71  303.42   611.5   312.7  616.31
  331.98  625.78   332.2  618.05   344.7   620.4   378.8  623.53   402.8  624.54
BR U #Mann= 3
       0    .012  259.71     .03   312.7     .04
BR U Banks=259.71,312.7
BR D #Sta/Elev= 30
       0  619.41    49.5  619.09    65.1   619.5      86   617.6    91.4  616.78
   107.2  616.25   127.2  616.18   156.9  618.29   187.8  617.73   211.9  618.31
   219.6  618.07   229.5  616.25  229.73  624.86  231.06  624.86   231.1  621.73
  240.12  619.78  241.48  615.51  259.81  615.23   264.2  611.89   276.2  608.54
   281.1  608.38   291.1  610.97  303.42   611.5  308.95 614.595  331.98  625.78
     332  615.13   341.9  615.81   345.5  616.37     390  617.82   402.8  618.56
BR D #Mann= 3
       0    .012  259.81     .03  308.95     .04
BR D Banks=259.81,303.42
BC Design=,, 0 ,, 0 ,,,,,,
BC Use User HTab Curves=0
BC User HTab FreeFlow(D)= 0

Type RM Length L Ch R = 1 ,1156    ,144.7,156.3,155
XS GIS Cut Line= 3
1644590.15617584 747490.599837831644397.08196246747297.957698904
1644305.01530986747206.097079244
#Sta/Elev= 30
       0  619.41    49.5  619.09    65.1   619.5      82  617.78      86   617.6
    91.4  616.78   107.2  616.25   127.2  616.18   136.2  616.65   156.9  618.29
   165.2  618.29   187.8  617.73   211.9  618.31     219  618.14   230.2  616.13
   238.7  615.92   240.2  615.19   252.2  615.07   276.2  608.54   281.1  608.38
     284  608.93   295.3  612.22   305.2  614.34   322.2  615.28   329.3   614.7
     332  615.13   341.9  615.81   345.5  616.37     390  617.82   402.8  618.56
#Mann= 3 ,0,0
       0     .07       0   252.2    .035       0   305.2     .07       0
#XS Ineff= 2 , 0
          230.04  629.18  331.98          630.16
Permanent Ineff=
       F       F
Bank Sta=252.2,305.2
XS Rating Curve= 0 ,0
Exp/Cntr=0.5,0.3

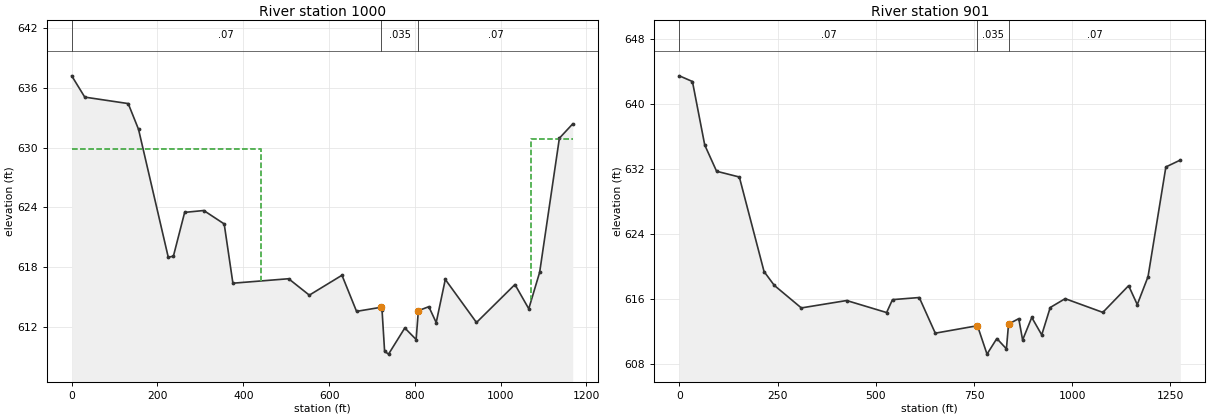
Type RM Length L Ch R = 1 ,1000    ,110.1,98.8,73.4
XS GIS Cut Line= 6
1645007.67995371747740.5112462211644541.89863589747234.824460543
1644518.22299249747201.5714440211644505.33223105747186.949334372
1644446.05820735747131.6398459121644203.94328587746894.114299887
#Sta/Elev= 30
       0  637.23    30.4  635.09   131.7  634.44   155.8  631.85   225.1  618.99
   237.1   619.1   263.3   623.5   307.9  623.69   355.5  622.34   375.8  616.38
   505.7  616.83     554  615.18   630.1  617.18   664.1  613.55  720.71613.9566
   723.5   613.7   729.5  609.53   738.7  609.25   776.6  611.88     803  610.72
   808.2  613.62   832.6  614.02   849.8  612.42     871  616.76   943.7  612.43
  1033.4  616.25  1065.6  613.81    1091  617.48    1137  630.96  1168.1   632.4
#Mann= 3 ,0,0
       0     .07       0  720.71    .035       0   808.2     .07       0
#XS Ineff= 2 , 0
          441.06  629.85 1070.82          630.85
Permanent Ineff=
       F       F
Bank Sta=720.71,808.2
XS Rating Curve= 0 ,0
Exp/Cntr=0.3,0.1

Type RM Length L Ch R = 1 ,901     ,202.7,183.1,200.4
XS GIS Cut Line= 6
1645094.46529865747673.4623152651644574.04884186747111.073063888
 1644567.8403802 747105.67714455 1644527.9411083747084.435736743
1644488.38327984747068.0602348411644186.97738589 746785.80866925
#Sta/Elev= 30
       0  643.46    33.3  642.76    64.6  634.94    94.8  631.71   152.7     631
   215.6  619.36   241.6  617.66   310.5  614.88   425.9  615.79   527.6  614.31
   542.6   615.9   610.7  616.16   651.5  611.77  758.88612.6896   783.2  609.19
   808.2  611.11   832.6  609.84     838  612.89     864  613.56   873.8  610.93
   897.1  613.71   922.5  611.56   944.1  614.93   982.1  616.02    1078  614.33
  1143.7  617.62  1165.7  615.29  1193.1  618.73  1238.5  632.24  1275.4  633.09
#Mann= 3 ,0,0
       0     .07       0  758.88    .035       0     838     .07       0
Bank Sta=758.88,838
XS Rating Curve= 0 ,0
Exp/Cntr=0.3,0.1